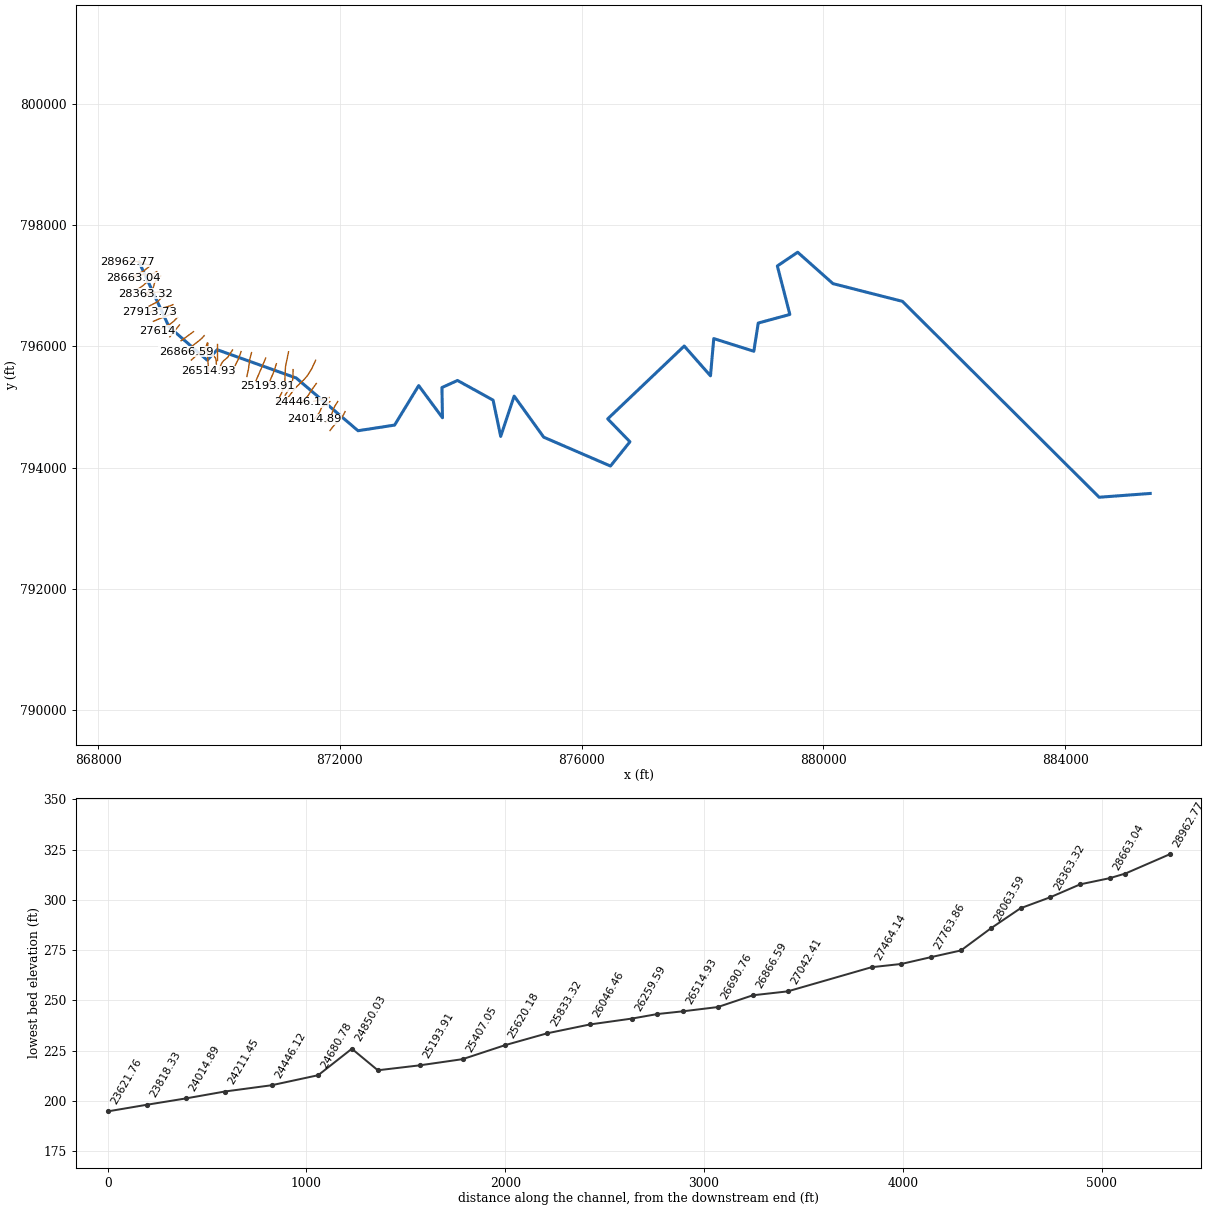
--- 11856_ras.prj (project) ---

Proj Title=11856
Current Plan=p01
Default Exp/Contr=0.3,0.1
English Units
Geom File=g01
Flow File=f01
Plan File=p01
Y Axis Title=Elevation
X Axis Title(PF)=Main Channel Distance
X Axis Title(XS)=Station
BEGIN DESCRIPTION:
RFD model 11856 exported to HEC-RAS
END DESCRIPTION:

--- 11856_ras.p01 (plan) ---

Plan Title=Plan 01
Program Version=4.10
Short Identifier=Plan 01
Geom File=g01
Flow File=f01
Subcritical Flow
Calc Critical at every XS
Secant Critical Depth

--- 11856_ras.f01 (steady flow) ---

Flow Title=Flow 01
Program Version=5.01
Number of Profiles= 6
Profile Names=10yr,25yr,50yr,100yr,100plus,500yr
River Rch & RM=11856,70,28962.77
  931.52 1273.95 1554.51 1747.71 2551.65  2953.4
River Rch & RM=11856,70,28740.87
  937.57  1283.1 1566.39 1761.77 2572.19 2976.49
River Rch & RM=11856,70,28513.18
  939.73 1286.36 1570.62 1766.79 2579.51 2984.71
River Rch & RM=11856,70,28363.32
  955.42 1309.79 1600.79 1802.31 2631.37 3042.06
River Rch & RM=11856,70,28213.45
  961.04 1318.27 1611.78 1815.31 2650.35 3063.25
River Rch & RM=11856,70,28063.59
  962.35 1320.23 1614.33 1818.31 2654.74 3068.14
River Rch & RM=11856,70,27913.73
  984.59 1353.63 1657.51 1869.31 2729.19 3150.68
River Rch & RM=11856,70,   27614
  994.05 1367.88 1675.96 1891.13 2761.05 3186.02
River Rch & RM=11856,70,27464.14
  996.67 1371.79 1681.02  1897.1 2769.76 3195.64
River Rch & RM=11856,70,27042.41
 1006.72 1387.05 1700.85 1920.64 2804.13 3233.97
River Rch & RM=11856,70,26866.59
  1193.3 1671.66 2072.55  2363.5 3450.71 3949.97
River Rch & RM=11856,70,26690.76
 1200.17  1682.2 2086.36 2380.01 3474.81 3976.45
River Rch & RM=11856,70,26514.93
 1208.95 1695.65 2103.98 2401.06 3505.55 4010.19
River Rch & RM=11856,70,26259.59
 1213.14 1702.07  2112.4 2411.12 3520.24 4026.29
River Rch & RM=11856,70,26046.46
 1217.33 1708.49 2120.81 2421.17 3534.91 4042.36
River Rch & RM=11856,70,25833.32
 1224.19 1718.98 2134.55 2437.59 3558.89 4068.61
River Rch & RM=11856,70,25620.18
    1356 1913.18 2383.34 2729.29 3984.76 4510.81
River Rch & RM=11856,70,25407.05
 1361.93 1922.27 2395.24 2743.51 4005.52 4533.17
River Rch & RM=11856,70,25193.91
 1367.42 1930.69  2406.3 2756.76 4024.87 4554.08
River Rch & RM=11856,70,24980.78
 1489.37 2116.45 2649.12 3046.46 4447.83 5003.89
River Rch & RM=11856,70,24850.03
 1493.33 2122.51 2657.07 3055.97 4461.72 5018.65
River Rch & RM=11856,70,24680.78
 1498.01 2129.67 2666.46 3067.21 4478.12 5036.07
River Rch & RM=11856,70,24446.12
 1502.32 2136.27 2675.12 3077.57 4493.25 5052.13
River Rch & RM=11856,70,24211.45
 1506.99 2143.42 2684.49 3088.78 4509.62 5069.51
River Rch & RM=11856,70,24014.89
 1521.09 2165.13 2713.05 3123.04 4559.63 5122.83
River Rch & RM=11856,70,23818.33
 1523.95  2169.5 2718.79 3129.91 4569.67 5133.46
River Rch & RM=11856,70,23621.76
 1559.42  2224.4 2791.26  3217.1 4696.96 5269.66
River Rch & RM=11856,70, 23425.2
 1561.81  2228.1 2796.15 3222.99 4705.56 5278.87
River Rch & RM=11856,70,23309.45
 1563.86 2231.28 2800.34 3228.04 4712.94 5286.76
River Rch & RM=11856,70,23132.99
 1569.14 2239.55 2811.34 3241.34 4732.36 5307.76
River Rch & RM=11856,70,22956.53
 1580.16 2256.74 2834.13 3268.88 4772.56 5350.98
River Rch & RM=11856,70,22780.08
 1581.81 2259.32 2837.56 3273.02 4778.62 5357.52
River Rch & RM=11856,70, 22576.3
 1586.49 2266.61 2847.22 3284.69 4795.65 5375.81
River Rch & RM=11856,70,22372.53
 1590.48 2272.85 2855.49 3294.68 4810.23 5391.46
River Rch & RM=11856,70,22168.76
 1595.27 2280.25 2865.26 3306.42 4827.38  5409.7
River Rch & RM=11856,70,21619.42
 1972.57 2829.61 3564.51 4121.45 6017.32 6563.82
River Rch & RM=11856,70,20870.04
 1979.02 2839.62 3577.75 4137.41 6040.62 6587.94
River Rch & RM=11856,70,20230.91
  2137.1 3075.68 3883.05 4498.31 6567.53 7105.51
River Rch & RM=11856,70,19797.91
 2140.84 3081.51 3890.79 4507.66 6581.18 7119.54
River Rch & RM=11856,70,19451.74
 2152.36 3099.47 3914.62 4536.46 6623.23 7162.74
River Rch & RM=11856,70,19268.31
 2153.92  3101.9 3917.84 4540.34  6628.9 7168.57
River Rch & RM=11856,70,18531.27
 2157.97  3108.2 3926.21 4550.45 6643.66 7183.72
River Rch & RM=11856,70,17364.81
 2173.32 3132.22 3958.14 4589.12 6700.11 7241.87
River Rch & RM=11856,70,17094.45
  2176.8 3137.77  3965.6 4598.21 6713.39  7255.8
River Rch & RM=11856,70,16595.98
 2877.97 4231.06 5417.98 6355.59 9279.16 9829.58
River Rch & RM=11856,70,16250.07
 2886.69 4244.86 5436.48 6378.16 9312.12 9862.51
River Rch & RM=11856,70,15144.06
 2934.94 4321.68 5539.84 6504.63 9496.7510047.99
River Rch & RM=11856,70,14070.76
 2951.48  4348.1 5575.48 6548.32 9560.5410112.23
River Rch & RM=11856,70,13686.19
  2961.7 4364.43 5597.51 6575.33 9599.9710151.92
River Rch & RM=11856,70,13443.22
 2970.65 4378.84 5617.03 6599.35 9635.0410187.49
River Rch & RM=11856,70,13200.24
 3020.68  4459.5 5726.37 6733.97  9831.610386.78
River Rch & RM=11856,70,12714.28
 5005.02 7142.33 8974.1710336.57 15091.414317.68
River Rch & RM=11856,70,11499.39
 5022.19 7171.11 9013.8710385.9915163.54 14387.8
River Rch & RM=11856,70,10770.46
 5045.93 7210.43 9067.79 10452.815261.0814481.68
River Rch & RM=11856,70,10041.52
 5113.61 7324.87  9226.410650.9815550.4314764.51
River Rch & RM=11856,70,9555.564
 5121.77 7338.68 9245.5710674.9515585.4314798.73
River Rch & RM=11856,70,9363.402
 5123.47 7341.55 9249.5410679.8915592.6414805.75
River Rch & RM=11856,70,8880.399
 5130.82 7354.11 9267.0310701.85 15624.7 14837.3
River Rch & RM=11856,70,8019.875
  5479.3  7872.5 9936.4411490.8716776.6715819.92
River Rch & RM=11856,70,7672.891
 5492.52 7894.31 9966.3211527.8716830.6915871.14
River Rch & RM=11856,70,6731.716
 5505.88 7917.43 9998.76 11568.816890.4415929.97
River Rch & RM=11856,70,6091.778
 5831.95 8427.8610678.3212391.16 18091.117007.23
River Rch & RM=11856,70,5590.233
 5942.88 8611.4510930.4212704.11   1854817437.71
Boundary for River Rch & Prof#=11856,70,1
Up Type= 0
Dn Type= 2
Boundary for River Rch & Prof#=11856,70,2
Up Type= 0
Dn Type= 2
Boundary for River Rch & Prof#=11856,70,2
Up Type= 0
Dn Type= 2
Boundary for River Rch & Prof#=11856,70,2
Up Type= 0
Dn Type= 2
Boundary for River Rch & Prof#=11856,70,2
Up Type= 0
Dn Type= 2
Boundary for River Rch & Prof#=11856,70,2
Up Type= 0
Dn Type= 2

--- 11856_ras.g01 (geometry) ---

Geom Title=11856
Program Version=4.10

River Reach=11856,70
Reach XY= 30
868677.441828125797390.323225798869173.491109766796320.191748327
869805.457169433795771.112108771869971.119409061795942.903631847
871278.830717016795476.087114665872300.532105902794607.163503557
872905.179199038794700.137048308873303.967588024795351.217874613
873697.575187638  794821.1159013873688.553458064795319.165588237
873946.365439238795436.156559122874534.907105905795111.503781331
874660.775161459794512.545448014874883.050928947795178.495629193
875372.580717013794500.392670233876476.747383683794024.698225783
876798.795994794 794424.87183689876430.740439236794802.476003567
877696.828956625 796003.68640737878131.261272567795512.545447999
878185.488888284796126.996442469 878848.27516146795917.927392448
878921.352430453796383.090904479879444.581251306796524.679211816
879237.328449287797324.458625743 879573.48130124797551.142863334
880157.302939237797033.378781338881306.608494792796740.844059109
884561.210636112793509.934047549885405.828691624793572.434047512

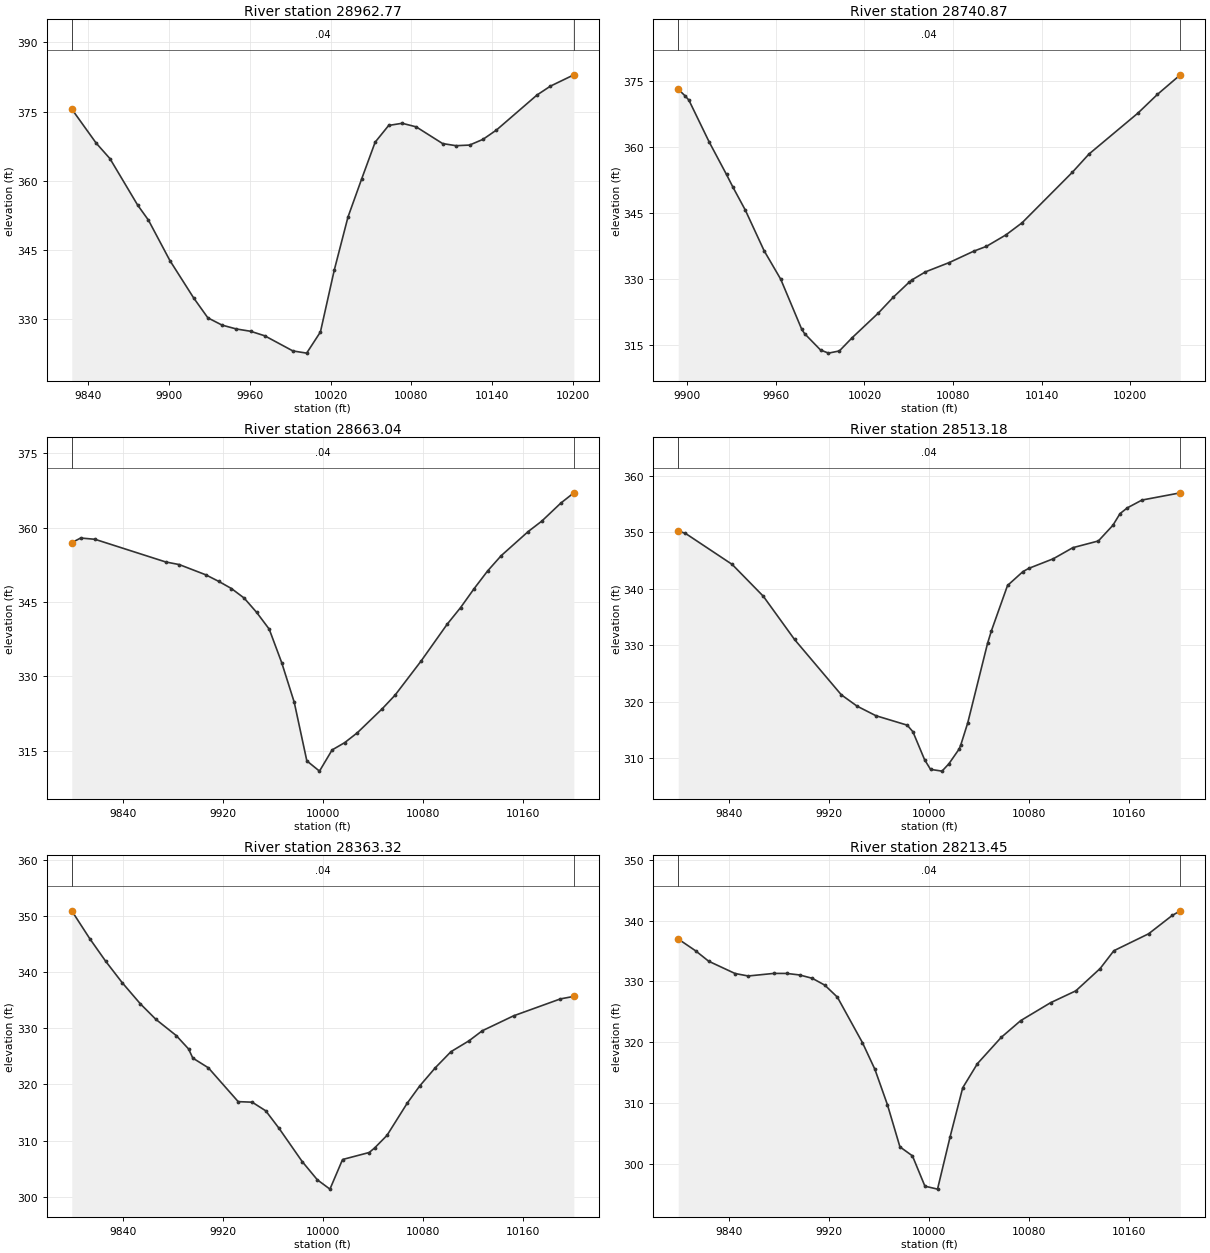
Type RM Length L Ch R = 1 ,28962.77,221.897200,221.897200,221.897200
XS GIS Cut Line= 6
868842.605334669797341.569665387 868771.71282357797358.755728677
868691.757000983797386.359524593868640.308143586797397.474494219
868539.311507702797402.867932975 868477.70324707797397.239060998
#Sta/Elev= 30
9827.588375.52449845.704 368.1719855.993364.79569876.573354.74029884.593351.4856
9900.534342.74369918.215334.64499928.794330.32679939.373328.75229949.953327.9187
9960.532327.42359971.111326.43829992.014323.162410002.25322.689710012.48 327.269
10022.72340.603210032.96352.1418 10043.1360.367910053.17368.359410063.23371.9855
 10073.3372.453110083.69371.677310103.37368.056410113.37367.599710123.37367.7338
10133.37368.974710143.39370.993410173.51378.569410183.55380.502610200.92 382.943
#Mann= 3 , 0 , 0
9827.588    0.04       09827.588    0.04       010200.92    0.04       0
#XS Ineff= 2 , 0
       0                               0
Bank Sta=9827.588,10200.92
Exp/Cntr=0.3,0.1

Type RM Length L Ch R = 1 ,28740.87,77.830000,77.830000,77.830000
XS GIS Cut Line= 6
868850.661301851797317.938828349868744.322535217797234.156769812
868643.326156318797190.328152552868631.884910256797183.097870231
868603.971018553797168.676486775868558.749687701797148.749420851
#Sta/Elev= 30
9893.977373.06589898.725371.52189901.184370.58929914.884361.11469926.646353.7062
9931.042350.80699939.377 345.6259952.107336.40029963.359329.92569977.569318.5654
9979.517317.5732  9990.3313.86279995.676313.153310003.03313.648310011.83316.6927
10029.36322.232810039.52325.835910050.42329.300410052.36329.813310061.32331.6012
10077.48333.724610094.02336.3017 10102.6337.393410115.82340.003110126.73342.7455
10160.74354.206910171.99358.343910205.14367.644310218.32371.885710233.82376.3333
#Mann= 3 , 0 , 0
9893.977    0.04       09893.977    0.04       010233.82    0.04       0
#XS Ineff= 2 , 0
       0                               0
Bank Sta=9893.977,10233.82
Exp/Cntr=0.3,0.1

Type RM Length L Ch R = 1 ,28663.04,149.863500,149.863500,149.863500
XS GIS Cut Line= 6
 868971.24677663797229.914498418 868869.41601967797181.425193635
 868823.61196001 797175.34461199868753.959036875797183.525368715
868722.476701176797181.204205251 868591.24492654797131.036125788
#Sta/Elev= 30
9799.082356.99449806.224357.92859817.658  357.679874.216353.09879885.131352.5639
9906.272350.50729916.685349.17539926.898347.72739937.048345.80379947.072 342.908
9957.096339.53339967.117332.75279977.137 324.7689987.223312.93569997.337310.8677
10007.44315.146610017.53316.623410027.61318.609610047.65323.482310057.75326.1846
10078.61333.078510099.56340.538110110.28  343.89 10121.1347.708510131.92351.2902
10142.74354.360110164.38359.236310175.21361.331910190.54364.991410200.91367.0511
#Mann= 3 , 0 , 0
9799.082    0.04       09799.082    0.04       010200.91    0.04       0
#XS Ineff= 2 , 0
       0                               0
Bank Sta=9799.082,10200.91
Exp/Cntr=0.3,0.1

Type RM Length L Ch R = 1 ,28513.18,149.863600,149.863600,149.863600
XS GIS Cut Line= 6
868939.591374929 797160.62439884 868826.90096811797076.468116533
868764.054607873797018.521742549868731.505228349796992.082300642
  868681.9132822796957.971811684868618.610748621796920.346534175
#Sta/Elev= 30
9799.026350.21589804.756349.80199842.198344.3074 9867.16 338.6749892.121331.0386
9929.564321.25889942.181319.25469957.239317.56359982.337315.88889986.883314.7267
9996.236309.7889   10001308.0699 10010.2307.762510015.72309.0687 10023.9311.6718
 10025.2312.379810030.78316.287710046.64330.344910049.74332.575110062.63340.5802
10075.03343.048510079.63343.6057 10099.3345.308110114.92347.266310135.36348.4527
   10147351.229110152.71353.293310158.63354.318310170.26355.685210200.96356.9638
#Mann= 3 , 0 , 0
9799.026    0.04       09799.026    0.04       010200.96    0.04       0
#XS Ineff= 2 , 0
       0                               0
Bank Sta=9799.026,10200.96
Exp/Cntr=0.3,0.1

Type RM Length L Ch R = 1 ,28363.32,149.863500,149.863500,149.863500
XS GIS Cut Line= 6
869036.327212774797160.168282986868981.634033454797113.627951582
868951.474706622 797076.88682445868933.053595148797039.357982137
868912.450434017796962.073345651868786.449067642796864.504869192
#Sta/Elev= 30
9799.091350.92889813.492345.97219826.206341.95679839.425338.13849854.008334.3562
9866.408 331.598 9882.66328.71829892.571326.32579895.938324.70329908.418322.9653
9932.263316.94249943.462316.8458 9954.31315.31029964.931312.19799983.473306.2738
9995.606303.018710005.69301.358610015.79306.633710037.07307.881910041.45308.6909
10051.32310.926510067.51 316.661 10077.5 319.72710090.02322.981310102.54325.8411
10116.94327.774510127.58329.563710152.61332.223510190.17335.244510200.87335.6893
#Mann= 3 , 0 , 0
9799.091    0.04       09799.091    0.04       010200.87    0.04       0
#XS Ineff= 2 , 0
       0                               0
Bank Sta=9799.091,10200.87
Exp/Cntr=0.3,0.1

Type RM Length L Ch R = 1 ,28213.45,149.863600,149.863600,149.863600
XS GIS Cut Line= 6
869138.089353288 796923.58903132869040.141259801 796895.21731885
868945.335916181796890.961836667868888.657936741796881.706691259
868843.194216149796862.302661363868759.420122377796811.917160805
#Sta/Elev= 30
 9799.08336.96219812.899335.03789823.456333.3125 9844.57 331.2969855.076 330.889
9875.626331.31349885.901 331.3089896.176331.05919906.342330.51329916.406329.3825
 9926.47327.41139946.525319.94059956.525315.53989966.526309.74199976.526302.8251
9986.526301.34699996.529296.367810006.62295.883610016.69304.480810026.77 312.527
10038.57316.498510057.58320.8048 10073.2323.562110097.04326.493910117.35328.4555
10136.76332.112710147.76335.039210175.56337.819710194.43340.826410200.94341.5909
#Mann= 3 , 0 , 0
 9799.08    0.04       0 9799.08    0.04       010200.94    0.04       0
#XS Ineff= 2 , 0
       0                               0
Bank Sta=9799.08,10200.94
Exp/Cntr=0.3,0.1

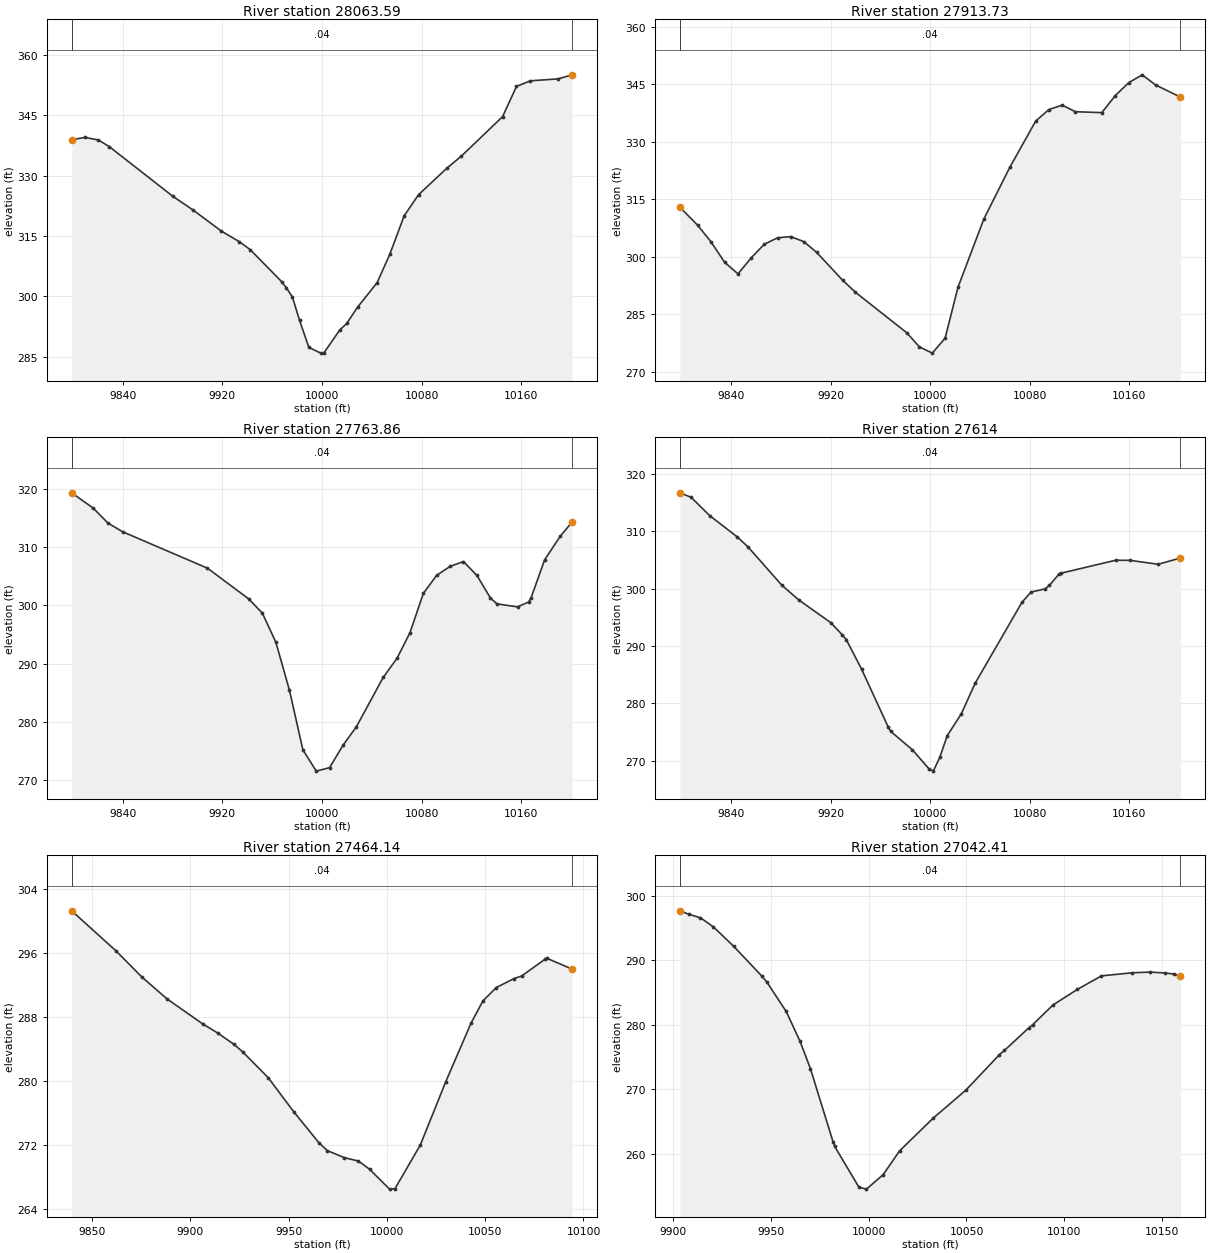
Type RM Length L Ch R = 1 ,28063.59,149.863500,149.863500,149.863500
XS GIS Cut Line= 6
869184.730920558796866.765301896869062.095460075796811.245293089
869032.170774495796788.625835768869002.186191025796750.529680041
868978.969979599796731.427838281868844.803197997796662.435490951
#Sta/Elev= 30
 9799.06338.88829809.632339.48639820.496338.84559829.158337.20939880.322 324.829
9896.647321.39779919.209316.19069933.766313.52049942.345311.58799967.609303.6232
9971.336302.11539976.224299.82459982.029293.96179989.482287.2641    9999285.8392
 10001.7285.959710014.26291.575610019.88293.209610028.58297.267310044.32303.3727
10054.51310.450310066.01319.984510077.52325.231810100.52331.897210111.66334.7506
10145.03344.655810156.16352.152610167.28353.555910189.53354.039310200.88355.0479
#Mann= 3 , 0 , 0
 9799.06    0.04       0 9799.06    0.04       010200.88    0.04       0
#XS Ineff= 2 , 0
       0                               0
Bank Sta=9799.06,10200.88
Exp/Cntr=0.3,0.1

Type RM Length L Ch R = 1 ,27913.73,149.863600,149.863600,149.863600
XS GIS Cut Line= 6
869238.057214576796686.839903249869195.533492798796669.054725925
869149.409036725796653.191967479869013.202816994796618.391570246
868962.554644281796603.275457117868856.640621233796562.179267141
#Sta/Elev= 30
9799.021 312.9199813.175308.26819824.014303.89229834.854298.59669845.679295.5477
9856.254299.73419866.829303.28959877.403304.95369887.978305.26959898.469303.9768
9908.852301.14999929.619293.92359939.999 290.7549981.145280.20789991.432276.4969
10001.71274.881610012.02278.785210022.33292.039410043.05309.804810063.92323.3097
10084.79335.421310095.38338.4145   10106339.564510116.63337.847610137.89337.6101
 10148.7342.054710159.51345.431710170.32347.467510181.13344.802610200.98341.6757
#Mann= 3 , 0 , 0
9799.021    0.04       09799.021    0.04       010200.98    0.04       0
#XS Ineff= 2 , 0
       0                               0
Bank Sta=9799.021,10200.98
Exp/Cntr=0.3,0.1

Type RM Length L Ch R = 1 ,27763.86,149.863500,149.863500,149.863500
XS GIS Cut Line= 6
869279.768631416796577.603753029869228.699114916796545.964644594
869167.962475841796515.181158083869121.075452066796495.129768485
 868989.41384127 796443.23720379868914.711240676796411.229265906
#Sta/Elev= 30
9799.041319.30459816.414316.66969828.178314.12049839.941312.62619908.108306.3781
9941.307301.09359952.183298.65989963.059293.65499973.936 285.4399984.731275.2237
9995.473 271.56710006.21 272.16910016.96 276.00610027.71279.177910049.21287.6379
10060.44290.955110070.71295.305110081.47302.051310092.22 305.16210102.97306.6907
10113.72307.513910124.52305.1309 10135.4301.240310140.64300.252810157.16299.7384
10166.03300.581610168.04301.316510178.92  307.8310191.42311.855110200.99314.3066
#Mann= 3 , 0 , 0
9799.041    0.04       09799.041    0.04       010200.99    0.04       0
#XS Ineff= 2 , 0
       0                               0
Bank Sta=9799.041,10200.99
Exp/Cntr=0.3,0.1

Type RM Length L Ch R = 1 ,   27614,149.863600,149.863600,149.863600
XS GIS Cut Line= 6
869310.984893263796475.441058376869253.272612573 796413.94856072
869204.921909571796375.753764056869169.666493062796354.799348404
869063.584757371796300.793464103868979.321974201796255.073881384
#Sta/Elev= 30
9799.042316.68069808.026315.90289823.037312.6892 9845.14308.99049853.695307.2589
9880.958300.55779894.341298.03299920.229294.04019929.379291.93939932.604291.1091
9944.979 285.9289966.123275.9416 9968.25275.10859985.695271.8913    9999268.5785
10002.54268.1611 10007.7270.540910013.77274.356410024.99278.140610036.21283.5055
10073.82297.6184 10081.1299.382410092.32299.933310095.86300.563210103.54302.5309
10105.13302.670110149.03 304.928 10160.4304.911710183.16304.223310200.99305.3172
#Mann= 3 , 0 , 0
9799.042    0.04       09799.042    0.04       010200.99    0.04       0
#XS Ineff= 2 , 0
       0                               0
Bank Sta=9799.042,10200.99
Exp/Cntr=0.3,0.1

Type RM Length L Ch R = 1 ,27464.14,421.720600,421.720600,421.720600
XS GIS Cut Line= 2
869347.133124186796352.578574711869186.336303819796155.064370166
#Sta/Elev= 27
9839.542301.31629862.209 296.2869875.104293.08069887.998290.32189906.277287.1742
9913.788 286.0589922.117284.63329926.683283.66739939.578280.45629952.472276.2323
9965.367272.33189969.635271.35419978.262270.47879985.474270.04689991.157269.0234
10001.31266.540110004.05266.589110016.95272.047310029.84279.919410042.74287.2617
10048.83290.068310055.63291.730510064.67 292.85510068.53293.172510080.51295.2827
10081.42295.382110094.23294.0291
#Mann= 3 , 0 , 0
9839.542    0.04       09839.542    0.04       010094.23    0.04       0
#XS Ineff= 2 , 0
       0                               0
Bank Sta=9839.542,10094.23
Exp/Cntr=0.3,0.1

Type RM Length L Ch R = 1 ,27042.41,175.828400,175.828400,175.828400
XS GIS Cut Line= 2
869578.832479518 796241.16030548869372.455458102 796090.49241868
#Sta/Elev= 30
9903.691297.62769908.436 297.0679914.138296.55789920.817295.13699931.097292.1441
 9945.58287.49719948.057286.60049957.961282.03519965.016277.41939970.343273.1647
9981.976261.74419982.724261.12579995.106254.80849998.935254.521610007.49256.7777
10015.89 260.46410032.85265.472310049.81269.893310066.77 275.33910069.39276.0066
10081.78279.494810083.73279.968210094.16283.043410106.54285.443810118.92287.5536
10134.61288.029910143.68288.139610151.57287.997810156.06287.823610159.21287.5182
#Mann= 3 , 0 , 0
9903.691    0.04       09903.691    0.04       010159.21    0.04       0
#XS Ineff= 2 , 0
       0                               0
Bank Sta=9903.691,10159.21
Exp/Cntr=0.3,0.1

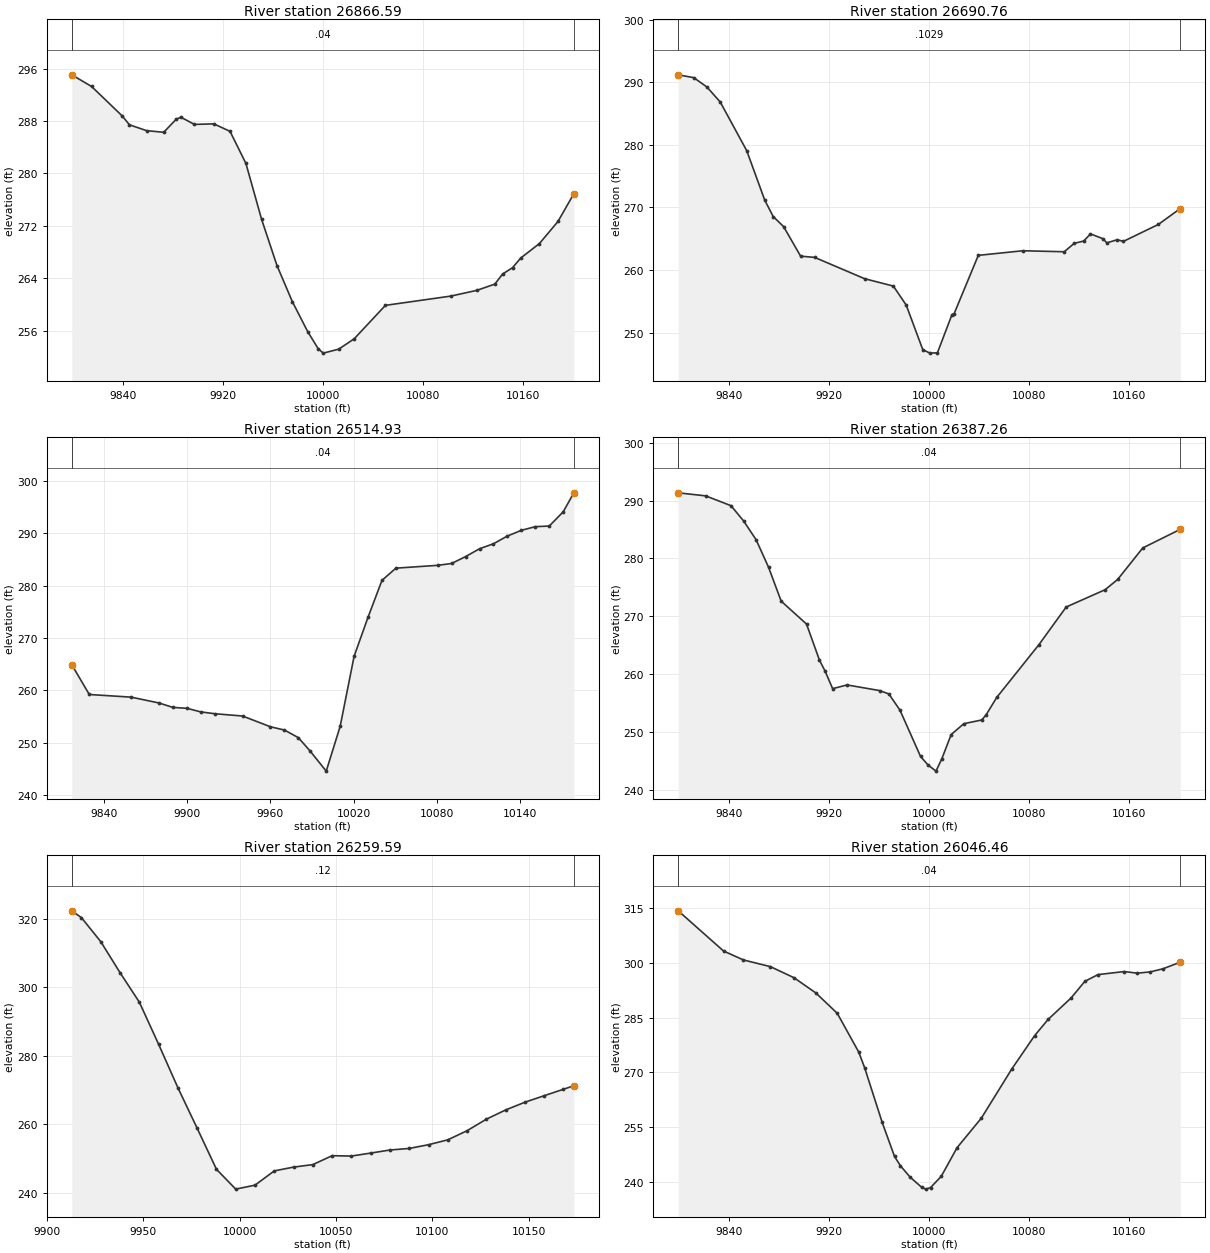
Type RM Length L Ch R = 1 ,26866.59,175.828500,175.828500,175.828500
XS GIS Cut Line= 6
869755.449274367796175.278958972869725.089195097796140.603327876
869682.519778824796100.753988056    869529.58994795984.026433418
869491.578671294795947.383560193869456.461531638795908.661341088
#Sta/Elev= 30
9799.048295.06749814.911293.28719839.293288.81489845.259287.43099858.957286.5415
9872.654286.29239882.601288.27469886.352 288.5999897.234287.49469912.752287.5807
 9925.74286.43669938.465281.52899951.003273.00259963.339 265.9299975.676260.4065
9988.013255.81659996.325253.238510000.35252.563710012.74253.167510025.15254.7565
10050.14259.860510102.27 261.26910123.31262.150110137.72263.104810143.94264.6418
10151.91265.618210158.49267.092910173.37269.290410188.26272.668410200.97 276.913
#Mann= 3 , 0 , 0
9799.048    0.04       09799.048    0.04       010200.97    0.04       0
#XS Ineff= 2 , 0
       0                               0
Bank Sta=9799.048,10200.97
Exp/Cntr=0.3,0.1

Type RM Length L Ch R = 1 ,26690.76,175.828400,175.828400,175.828400
XS GIS Cut Line= 6
869807.858441721796056.730125241869780.010251131795977.101528322
 869753.80509149795934.398638898869727.338655968795911.882136708
869622.507393554795844.524580439 869542.44417053 795772.56472073
#Sta/Elev= 30
9799.151291.17019811.577290.71889822.171289.21669832.765286.82859853.953279.0592
9868.394271.14629875.141268.53439883.508266.91549897.103262.19899908.336262.0053
9948.316258.60069971.315257.41999981.583254.39429994.873247.259610000.59246.7107
10006.57246.761710018.25252.872110019.95253.0158 10039.3262.330910074.98263.0649
10108.08262.906310116.04264.248110123.68264.620510129.07265.759110139.28264.9729
 10142.1264.326710150.47264.822210155.46264.567910183.41267.270310200.96 269.813
#Mann= 3 , 0 , 0
9799.151  0.1029       09799.151  0.1029       010200.96  0.1029       0
#XS Ineff= 2 , 0
       0                               0
Bank Sta=9799.151,10200.96
Exp/Cntr=0.3,0.1

Type RM Length L Ch R = 1 ,26514.93,127.669000,127.669000,127.669000
XS GIS Cut Line= 2
869800.596589863795947.572534744869830.978534307795587.329479189
#Sta/Elev= 30
9816.982264.93019829.599259.23539859.706258.73019879.777257.61689889.812256.7656
9899.848 256.6039909.883255.90859919.919255.5629 9939.99255.12229960.061253.0666
9970.096252.44659980.132250.99059988.372248.5086 10000.2244.594510010.24 253.147
10020.27266.530310030.31273.998310040.34281.038610050.38283.374310080.49283.9142
10090.52284.267110100.56285.585910110.59287.080410120.63288.032110130.66289.5113
 10140.7290.600310150.74291.301910160.77291.417710170.81294.1255 10178.5297.7658
#Mann= 3 , 0 , 0
9816.982    0.04       09816.982    0.04       0 10178.5    0.04       0
#XS Ineff= 2 , 0
       0                               0
Bank Sta=9816.982,10178.5
Exp/Cntr=0.3,0.1

Type RM Length L Ch R = 1 ,26387.26,127.669100,127.669100,127.669100
XS GIS Cut Line= 6
869817.663185023796046.519166292869807.715099246795972.514733731
869816.292387262795926.161817832869937.421737988795814.916961673
869953.703489334795767.252001588869956.964836447795704.985924864
#Sta/Elev= 30
9799.214291.33089821.165290.80599841.436289.10549851.466286.48079861.497283.2309
9871.527278.43589881.557 272.6129901.824268.65619912.207262.40399916.581260.5692
9922.723257.4904 9934.25258.13549960.243257.16259967.725256.57479976.581253.7767
9993.015245.7893    9999244.307810005.39243.240710010.07245.374310017.54249.5614
10027.67251.439710041.84252.073810045.28252.891310053.99255.976410087.81265.1151
10109.56271.601510140.68274.587910150.72276.3663 10170.8 281.80810200.83285.0244
#Mann= 3 , 0 , 0
9799.214    0.04       09799.214    0.04       010200.83    0.04       0
#XS Ineff= 2 , 0
       0                               0
Bank Sta=9799.214,10200.83
Exp/Cntr=0.3,0.1

Type RM Length L Ch R = 1 ,26259.59,213.135900,213.135900,213.135900
XS GIS Cut Line= 2
869969.867423196796030.037812522869969.867423196795769.621145855
#Sta/Elev= 28
9912.943 322.353 9917.98 320.344 9927.98313.3483 9937.98304.2817 9947.98 295.668
 9957.98283.3562 9967.98270.6529 9977.98258.7976 9987.98246.8113 9997.98240.9985
10007.98242.156610017.98 246.32610027.98 247.43910037.98248.164410047.98 250.773
10057.98250.664910067.98251.537710077.98252.432610087.98252.891510097.98 253.984
10107.98255.407310117.98258.079910127.98261.445910137.98264.139910147.98266.4049
10157.98268.308110167.98270.190810173.36271.2286
#Mann= 3 , 0 , 0
9912.943    0.12       09912.943    0.12       010173.36    0.12       0
#XS Ineff= 2 , 0
       0                               0
Bank Sta=9912.943,10173.36
Exp/Cntr=0.3,0.1

Type RM Length L Ch R = 1 ,26046.46,213.135900,213.135900,213.135900
XS GIS Cut Line= 6
870224.319497246795939.142536977870144.092339561795817.194623037
870077.771207036795762.345209353  870051.2912287 795731.60393416
870027.289294491795684.814390997870005.980030617795611.698117908
#Sta/Elev= 30
9799.085314.25189835.358303.24639851.242300.80049872.908298.96189891.683295.9445
9909.157291.78499926.355286.18999943.553275.56529948.208 271.3459962.309 256.314
9972.194246.98049976.954244.4173 9984.74241.29599994.048 238.505 9997.07238.0397
   10001238.455710009.58241.545710022.24249.394110041.66257.472610065.98270.9125
10084.25280.044310095.08284.508410113.54290.403110124.51294.945110135.04296.7867
10156.09297.624910166.51297.179110176.84297.525910187.17298.392410200.91 300.198
#Mann= 3 , 0 , 0
9799.085    0.04       09799.085    0.04       010200.91    0.04       0
#XS Ineff= 2 , 0
       0                               0
Bank Sta=9799.085,10200.91
Exp/Cntr=0.3,0.1

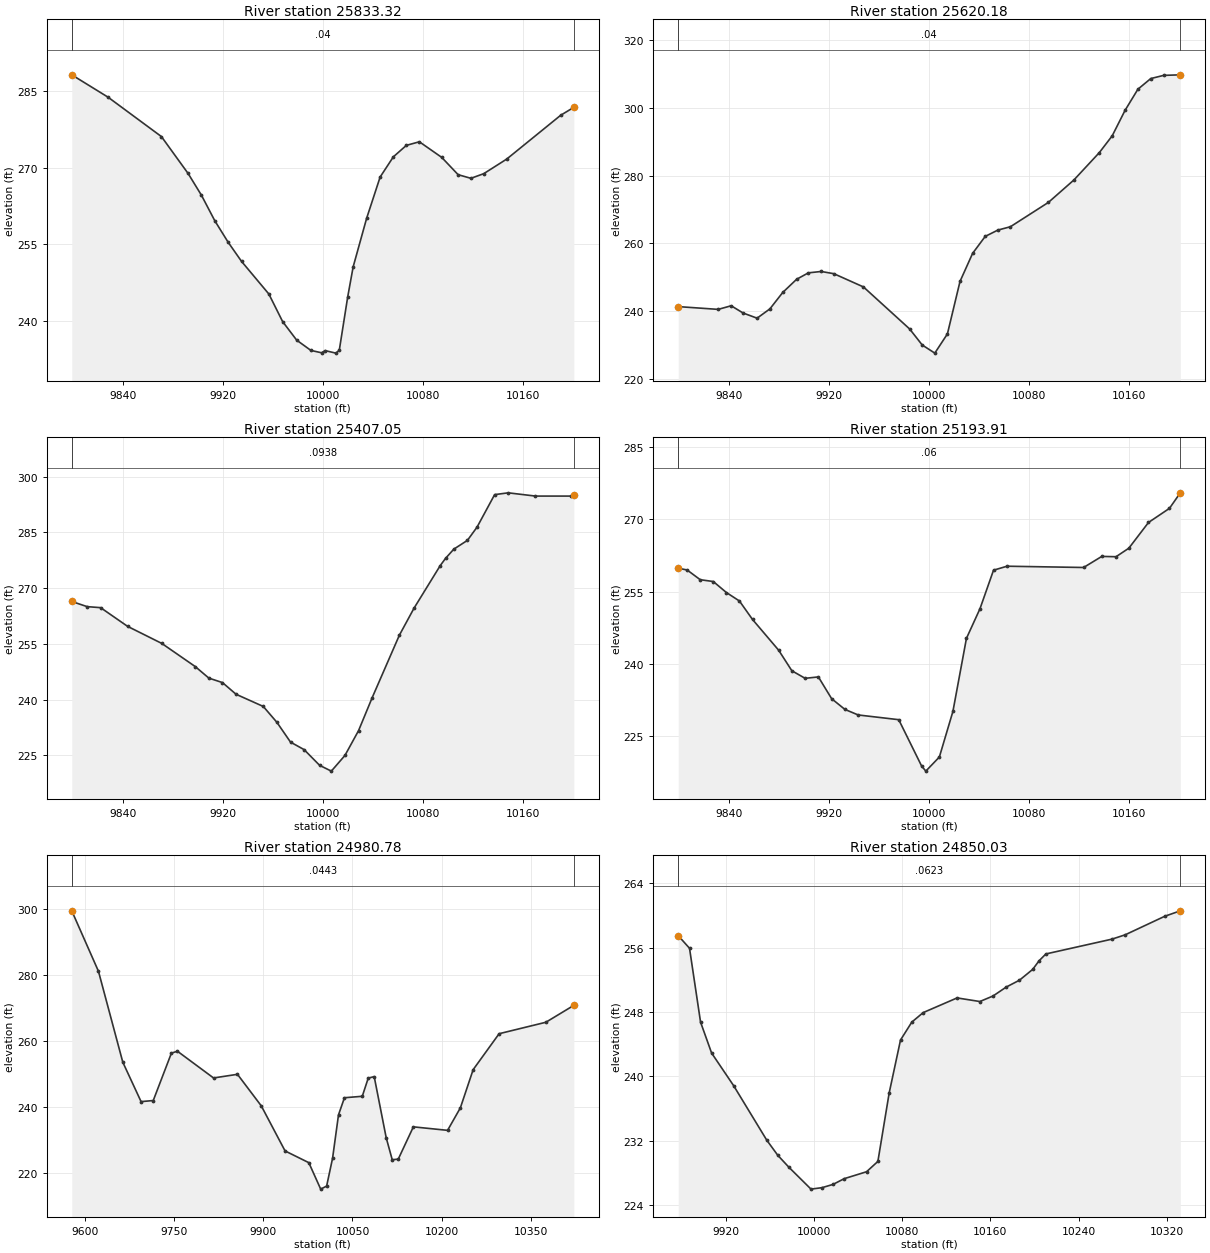
Type RM Length L Ch R = 1 ,25833.32,213.135900,213.135900,213.135900
XS GIS Cut Line= 6
870366.468434592795912.167208132870316.877669177795780.545250231
870280.571505758795709.046045294870269.118293501 795681.19393963
870256.557078536795637.800363896870233.063118751795534.672292012
#Sta/Elev= 30
9799.021288.14169828.052283.76869870.797276.05479892.169268.82989902.856264.5657
9913.542259.57379924.228255.36789934.914 251.635  9956.8245.24229967.816239.8495
9979.078 236.2149990.454234.2024    9999233.741710001.86234.166910010.42 233.673
10013.17234.2142 10019.9 244.64610024.28250.550510035.09260.0744 10045.9268.1475
10056.46272.089710066.88274.335210077.29275.037310095.19 271.98410108.32268.5967
10118.58 267.88810128.83268.796610147.22271.653210190.37280.216510200.96281.7834
#Mann= 3 , 0 , 0
9799.021    0.04       09799.021    0.04       010200.96    0.04       0
#XS Ineff= 2 , 0
       0                               0
Bank Sta=9799.021,10200.96
Exp/Cntr=0.3,0.1

Type RM Length L Ch R = 1 ,25620.18,213.135900,213.135900,213.135900
XS GIS Cut Line= 6
870539.136550476795895.785030035870522.779941104795837.967162782
 870510.87628369795786.290632159870503.134391414795740.602891275
870487.462306932795620.131884515870461.275160963795502.009002117
#Sta/Elev= 30
9799.019 241.4259831.012 240.6149841.405241.6769 9850.95239.54379862.151238.0229
9872.413240.76229882.674245.58679893.765249.46089903.198251.35939913.445251.7632
9923.587251.11389947.308247.21459984.278234.85099994.356230.133310004.43227.7414
10014.52233.395910024.61248.8424 10034.7257.094510044.79262.084210054.87263.9373
10064.96264.929310095.39272.092410115.79278.685710136.18286.752310146.45291.6741
10156.74299.168310167.03305.389210177.32 308.52110187.61309.460410200.98309.6227
#Mann= 3 , 0 , 0
9799.019    0.04       09799.019    0.04       010200.98    0.04       0
#XS Ineff= 2 , 0
       09954.211                       0
Bank Sta=9799.019,10200.98
Exp/Cntr=0.3,0.1

Type RM Length L Ch R = 1 ,25407.05,213.135900,213.135900,213.135900
XS GIS Cut Line= 5
870772.270310826  795806.3889815870740.345417124795728.293459764
870694.385108137795622.194644078870693.604273859795620.353367936
 870614.24371489795436.780110555
#Sta/Elev= 30
9799.005266.40119811.309265.01459822.113264.73789843.719 259.7099871.073255.1244
9897.861248.90369908.759   245.89919.657244.59539930.555241.45359952.351238.1757
9963.249233.91089974.147228.59189985.045226.56679997.453222.345410006.83220.7901
10017.73 225.01210028.62231.679310039.52 240.534 10061.3257.336110073.08264.6277
10093.99276.034610098.28277.997110104.88280.470910115.78282.827810123.49286.3901
10137.57295.128110148.46295.611410170.25294.737510199.09294.737410200.99295.0779
#Mann= 3 , 0 , 0
9799.005  0.0938       09799.005  0.0938       010200.99  0.0938       0
#XS Ineff= 2 , 0
       0                               0
Bank Sta=9799.005,10200.99
Exp/Cntr=0.3,0.1

Type RM Length L Ch R = 1 ,25193.91,213.135900,213.135900,213.135900
XS GIS Cut Line= 6
870949.503558587795711.819287592870924.579296684  795631.2159417
870903.827095876795573.132083802870883.013595701795523.374748522
870882.202205558795521.546731554870805.186873241795336.980715425
#Sta/Elev= 30
9799.016259.87379806.154259.50259816.621257.48669827.088257.11029837.556254.8296
9848.023253.0652 9858.49 249.2319879.424242.84739889.986238.58529900.605237.0155
9911.224237.30359921.843232.78139932.462230.55969943.081229.40799975.559228.4267
9993.853218.81679997.238217.747510008.09220.680610018.93 230.14410029.77245.3163
 10040.6251.465910051.44259.461310062.27260.288510123.57260.023710138.12262.3224
10149.54262.260510159.79264.030910175.51269.3704 10192.3272.301310200.99275.5241
#Mann= 3 , 0 , 0
9799.016    0.06       09799.016    0.06       010200.99    0.06       0
#XS Ineff= 2 , 0
       0                               0
Bank Sta=9799.016,10200.99
Exp/Cntr=0.3,0.1

Type RM Length L Ch R = 1 ,24980.78,130.748000,130.748000,130.748000
XS GIS Cut Line= 6
871150.922311709 795908.82804707871100.127344613795660.310731039
871089.694072878 795431.12362708871078.243938369795351.450597977
871035.238043457795226.695810629870966.474256749795093.488897011
#Sta/Elev= 30
9577.018299.46299621.978281.1779 9663.01253.65629693.785241.73459714.301242.0636
9744.916256.41339755.054256.98129815.887248.8941 9856.19249.99689896.349240.4398
9936.414226.81179976.419223.26339996.422 215.25910006.42216.178610016.43 224.595
10026.43237.731410036.44242.908110066.48243.348810076.53248.851910086.58249.2976
10106.79 230.80410116.95224.156910127.11224.335610152.56234.1017 10210.2233.0436
10231.74239.846510253.29251.406210297.04262.282610375.79265.745610422.95270.8628
#Mann= 3 , 0 , 0
9577.018  0.0443       09577.018  0.0443       010422.95  0.0443       0
#XS Ineff= 2 , 0
       09899.339        10043.35       0
Bank Sta=9577.018,10422.95
Exp/Cntr=0.3,0.1

Type RM Length L Ch R = 1 ,24850.03,169.252000,169.252000,169.252000
XS GIS Cut Line= 5
 871226.97509378795615.217167172871222.965804699795505.964039724
871219.958837889795455.847926216871194.900781135795345.592476498
871094.668554118795193.239491433
#Sta/Elev= 30
9877.105257.49039887.329255.92359897.336246.73619907.342242.89139927.356238.8212
9957.376232.04219967.383230.1599 9977.39228.68329997.415 225.96210007.43226.1456
10017.45226.552810027.47227.261510047.76228.123910058.02229.408810068.27237.9389
10078.53244.510810088.78246.741310099.04  247.92 10129.8249.747410150.41249.2998
10162.38249.986710174.35   251.110186.32251.952110198.29253.295510204.11254.3712
10210.26255.217610270.11257.058510282.08257.5968   10318259.906310332.07260.5816
#Mann= 3 , 0 , 0
9877.105  0.0623       09877.105  0.0623       010332.07  0.0623       0
#XS Ineff= 2 , 0
       0                10043.89       0
Bank Sta=9877.105,10332.07
Exp/Cntr=0.3,0.1

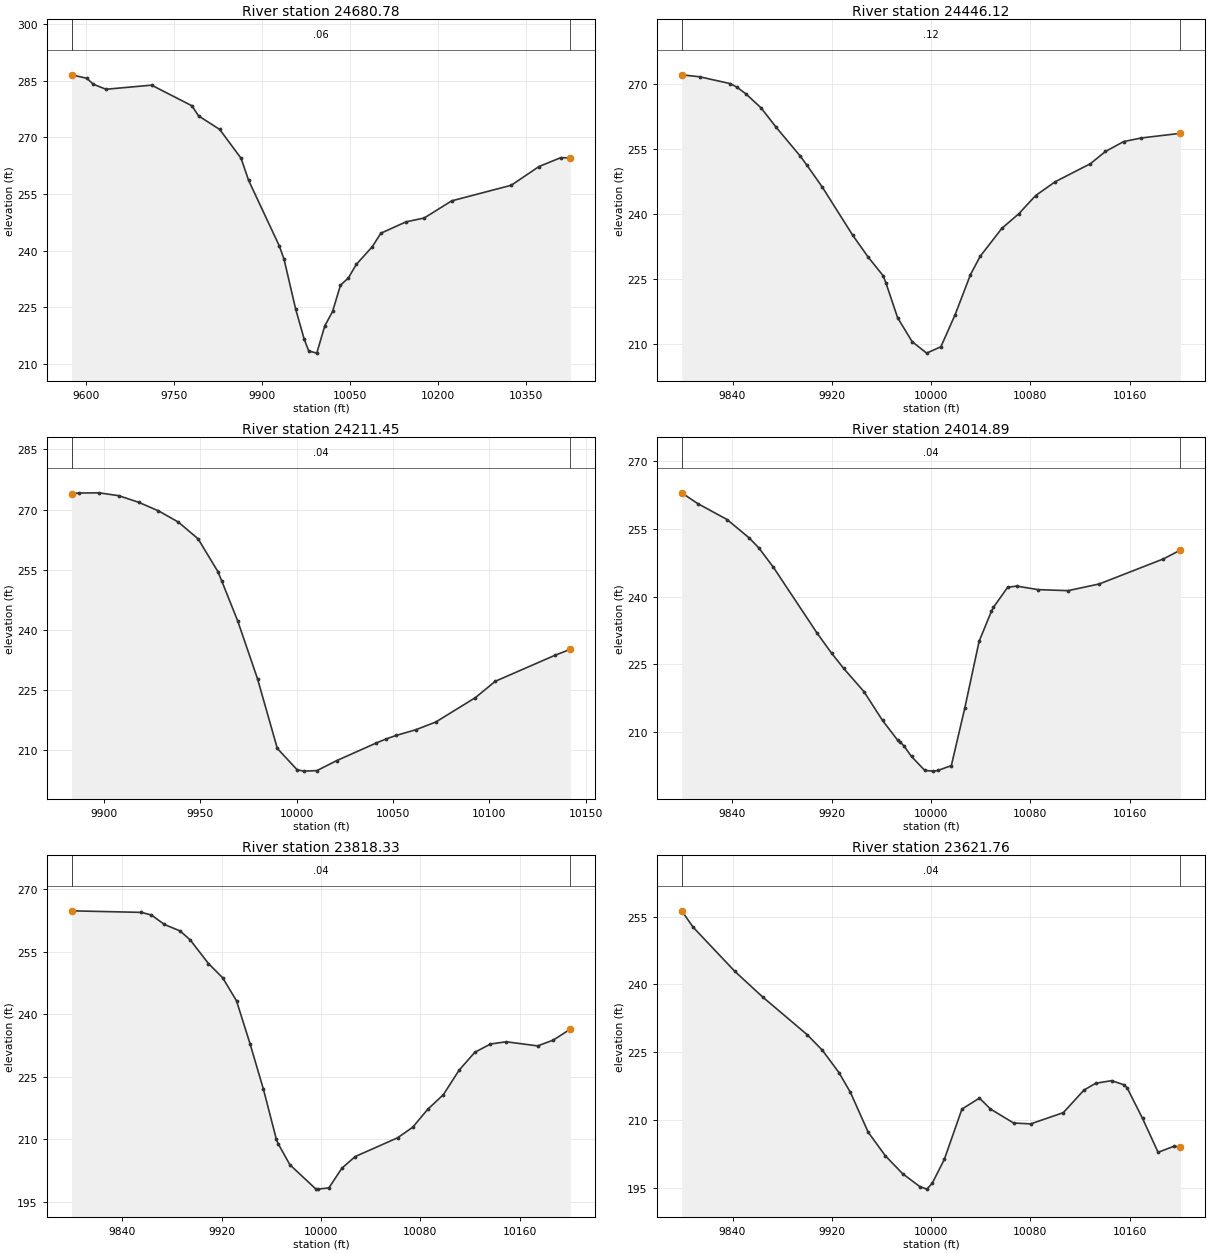
Type RM Length L Ch R = 1 ,24680.78,234.660500,234.660500,234.660500
XS GIS Cut Line= 6
871599.076431211795768.920724034871532.717841307795625.985876189
871463.384851189795516.290445739871405.871778314795449.197241588
871258.601879773795307.759372472871096.100954702795091.577484691
#Sta/Elev= 30
9574.621286.56449600.615285.65139611.482284.09039633.216282.73719711.052283.8295
9779.728278.37049791.306275.67189827.328272.0833 9863.78264.42429876.574258.5825
9929.106241.16099937.049237.67419956.693 224.5649971.325216.53349979.142213.3812
 9992.84212.809610006.34 219.96310019.79223.860110033.24 230.80610046.69232.7222
10060.14 236.29810087.59241.030910102.09244.578210144.87 247.591 10176.1248.6238
10222.99 253.16710324.65257.3034 10371.9262.260410408.87264.603410425.41264.5543
#Mann= 3 , 0 , 0
9574.621    0.06       09574.621    0.06       010425.41    0.06       0
#XS Ineff= 2 , 0
       0                               0
Bank Sta=9574.621,10425.41
Exp/Cntr=0.3,0.1

Type RM Length L Ch R = 1 ,24446.12,234.660500,234.660500,234.660500
XS GIS Cut Line= 6
871610.984733563795386.743908945871517.615069026795257.468147293
871486.469727745795204.570397575871469.186828861795180.630444462
871426.031685453795133.555033244871361.878377998795073.834221426
#Sta/Elev= 30
 9799.04272.09619813.527271.64349838.198270.0625 9843.42269.25669850.533267.7558
9862.869264.50139875.204259.95739894.658253.29159899.875251.23769912.211246.2116
9936.882235.01889949.217230.02229961.387225.67089963.589224.02719973.051215.9638
9984.715 210.4539996.379207.802910007.89209.2748 10019.4216.7185 10031.7225.9273
 10039.5230.150510057.06236.647710070.63239.9878 10084.2244.198410100.02247.3982
10128.36251.566710140.52254.3907 10155.2256.684810169.35257.508810200.94258.5851
#Mann= 3 , 0 , 0
 9799.04    0.12       0 9799.04    0.12       010200.94    0.12       0
#XS Ineff= 2 , 0
       0                               0
Bank Sta=9799.04,10200.94
Exp/Cntr=0.3,0.1

Type RM Length L Ch R = 1 ,24211.45,196.564100,196.564100,196.564100
XS GIS Cut Line= 2
 871818.82575653795153.301701411871567.089645419795092.537812522
#Sta/Elev= 26
9883.174273.99429887.109274.12329897.396274.17439907.684273.45939917.971 271.815
9928.258269.67929938.545266.88589948.832262.6997 9959.12 254.5149961.172252.1126
9969.407242.20659979.694227.76399989.981210.370210000.27205.031410003.79204.6959
10010.56204.825310020.84207.325410041.42211.731810046.41212.7208 10051.7213.6064
10061.99215.043710072.28216.961910092.85223.052110103.14227.1211   10134 233.591
10142.14235.1071
#Mann= 3 , 0 , 0
9883.174    0.04       09883.174    0.04       010142.14    0.04       0
#XS Ineff= 2 , 0
       0                               0
Bank Sta=9883.174,10142.14
Exp/Cntr=0.3,0.1

Type RM Length L Ch R = 1 ,24014.89,196.564100,196.564100,196.564100
XS GIS Cut Line= 6
871835.129940764  795087.4196165871704.270034117794996.973015429
871693.260079104 794980.67748965871676.756712392794937.280199678
871655.636708825794899.591635282871574.280251982 794794.38293702
#Sta/Elev= 30
9799.197263.01239812.036260.63699835.686257.09259853.472253.02319861.302250.7915
9873.055246.48869908.314231.84769920.066227.36539929.606224.06099946.008 218.888
9960.942212.49879973.011208.1593 9975.12207.75759978.228206.81689984.296204.4974
9994.983201.400710001.94201.248410005.65201.400610016.38202.483210027.28 215.345
10038.74230.064210048.71236.7613 10050.2237.570410061.67 242.02810068.96242.3208
10086.13241.529610110.41241.300210135.57242.790110187.22248.352210200.93250.3179
#Mann= 3 , 0 , 0
9799.197    0.04       09799.197    0.04       010200.93    0.04       0
#XS Ineff= 2 , 0
       0                               0
Bank Sta=9799.197,10200.93
Exp/Cntr=0.3,0.1

Type RM Length L Ch R = 1 ,23818.33,196.564200,196.564200,196.564200
XS GIS Cut Line= 6
871965.554758565  795088.9340281871925.840800992795027.583206077
871899.188208535794979.185521017871867.046943051794888.326031562
871855.799405901794864.739330625871765.103996646794744.152953862
#Sta/Elev= 30
9799.052264.8297 9855.28264.4572  9863.3263.83539873.878 261.555  9886.5260.0019
9894.608257.85359909.332252.18979920.748248.78589931.926243.25719942.772233.0045
9953.618222.05359964.031210.04939965.515208.97789974.966203.92379995.897198.1121
9997.467198.093310006.37198.391610016.86203.125810027.55205.902810061.78210.4112
10073.88212.928510085.98217.2262 10098.6220.745710111.26226.603310123.92230.9034
10136.58232.892310149.23233.427810174.55 232.44310187.21233.835910200.94236.4717
#Mann= 3 , 0 , 0
9799.052    0.04       09799.052    0.04       010200.94    0.04       0
#XS Ineff= 2 , 0
       0                               0
Bank Sta=9799.052,10200.94
Exp/Cntr=0.3,0.1

Type RM Length L Ch R = 1 ,23621.76,196.564100,196.564100,196.564100
XS GIS Cut Line= 6
872086.118834823794923.197733178872059.278268573794869.445601063
872030.236981938794825.143952054871909.978501542794702.090588216
871874.393406598794659.594435252871837.615688275794610.571621004
#Sta/Elev= 30
9799.041256.26299808.204  252.669841.736242.92969864.285237.23199900.036 228.937
9912.335225.48959925.734220.54969935.035 216.1419949.288207.38569963.198202.1373
9977.108198.19619991.017195.3343 9996.64194.7938   10001196.1281 10010.7201.3914
10024.87212.473910038.95214.900610047.88212.483610066.49209.400110080.26209.2023
10106.56211.689710123.17216.661310132.64218.174810145.44218.750610155.35217.8496
10157.94217.186710170.44210.394410182.94202.930310195.44204.231310200.98204.1748
#Mann= 3 , 0 , 0
9799.041    0.04       09799.041    0.04       010200.98    0.04       0
#XS Ineff= 2 , 0
       0                10034.11       0
Bank Sta=9799.041,10200.98
Exp/Cntr=0.3,0.1