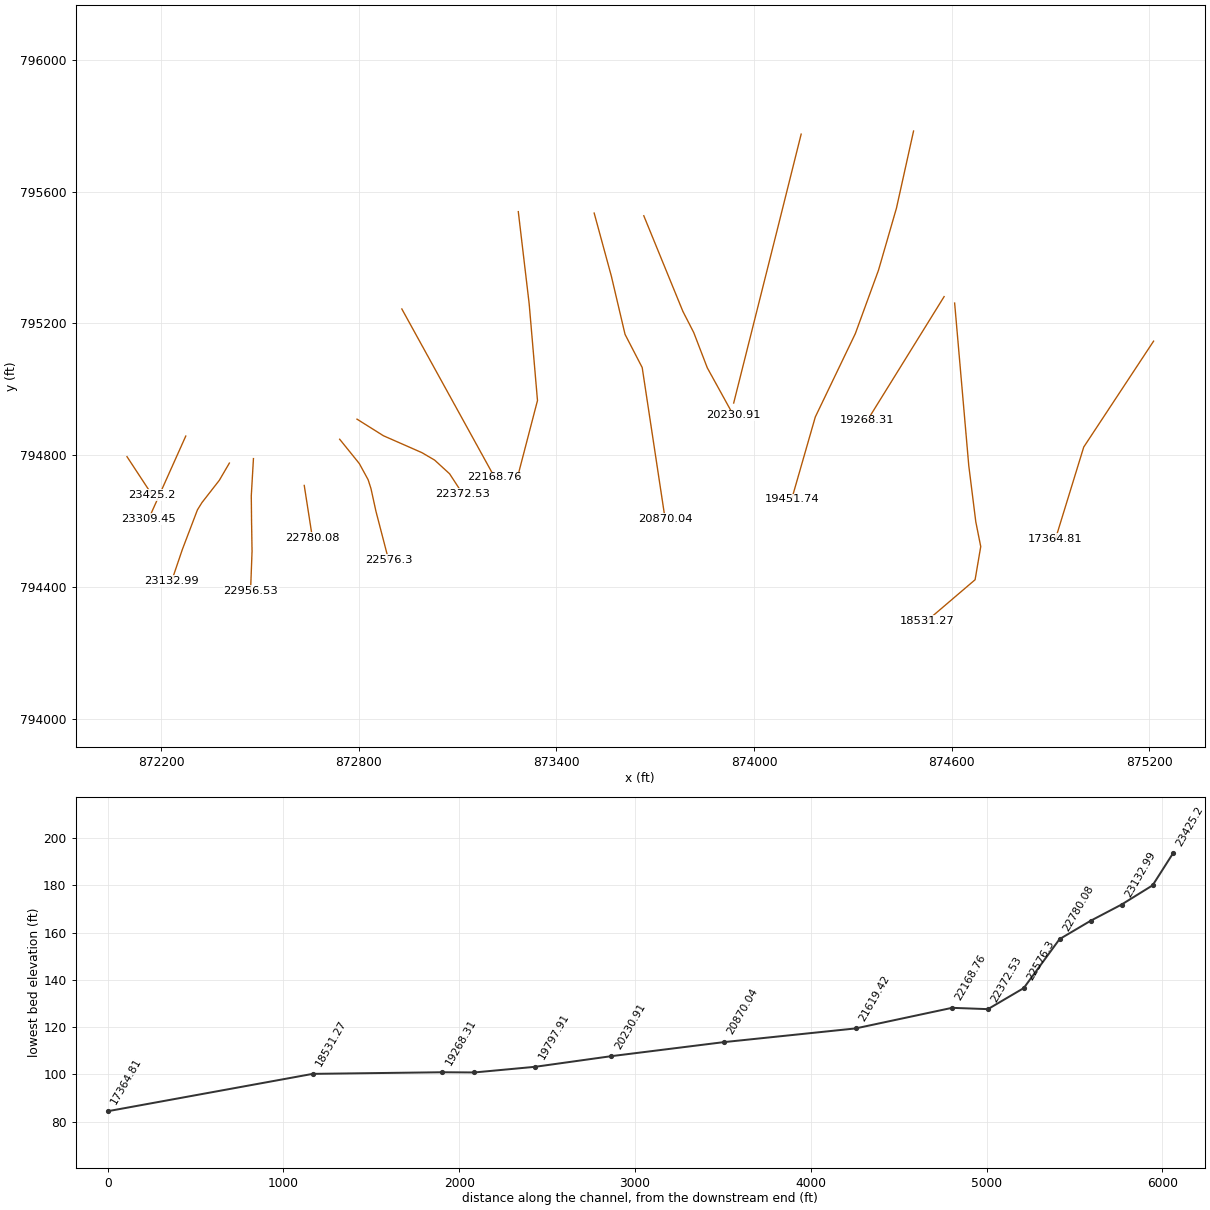
HEC-RAS study 11856_ras.prj: 11856

--- 11856_ras.g01 (geometry) --- (continued)

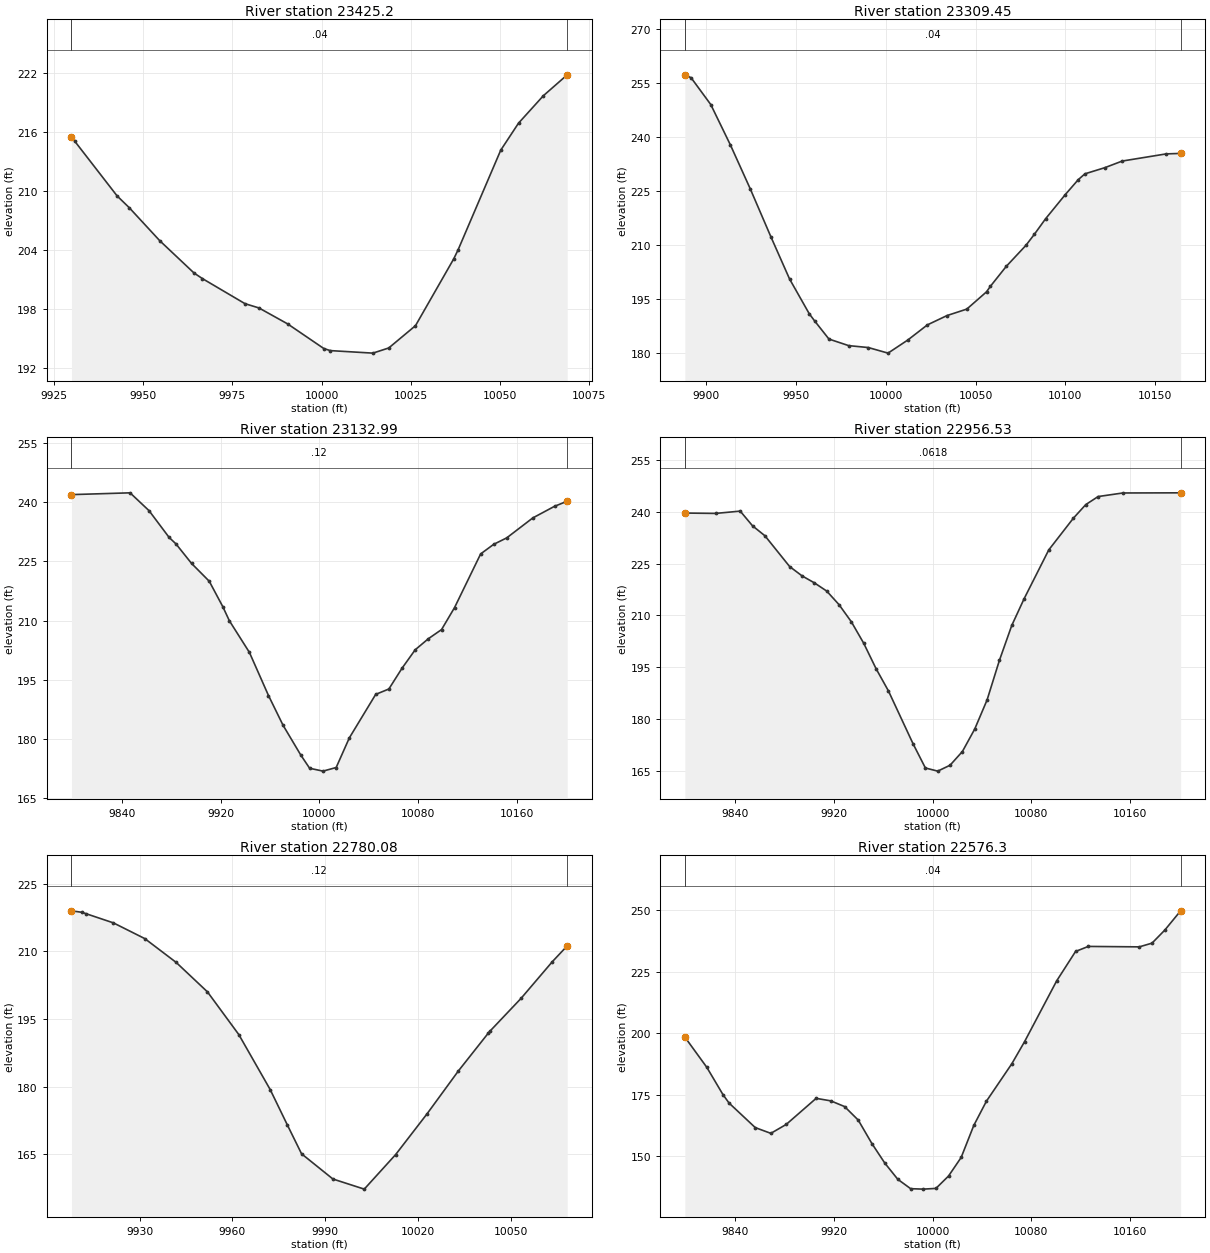
Type RM Length L Ch R = 1 , 23425.2,115.752500,115.752500,115.752500
XS GIS Cut Line= 2
872096.111951977794795.720464682872172.500840866794679.401020237
#Sta/Elev= 21
9929.808 215.509 9930.67215.06469942.634209.4669    9946208.28629954.597204.9162
9964.217  201.639966.561201.06549978.524198.51219982.434198.07899990.488196.4564
10000.65193.950110002.45193.739610014.42193.482610018.87194.006510026.38196.2748
10037.09203.054310038.34203.989610050.31214.1262 10055.3 216.87110062.27219.6616
10068.97221.7878
#Mann= 3 , 0 , 0
9929.808    0.04       09929.808    0.04       010068.97    0.04       0
#XS Ineff= 2 , 0
       0                               0
Bank Sta=9929.808,10068.97
Exp/Cntr=0.3,0.1

Type RM Length L Ch R = 1 ,23309.45,176.456800,176.456800,176.456800
XS GIS Cut Line= 2
872274.554923196794858.162812522872161.707700974794606.426701411
#Sta/Elev= 30
9888.222257.20139891.688256.39449902.647248.94859913.606 237.7019924.564225.6192
9936.027212.33429946.482200.55519957.441190.90169960.473188.88819968.399183.8831
9979.358182.06249990.317181.526610001.28179.978610012.23183.599310023.19187.8209
10034.15190.412610045.11192.197710056.07196.982410058.26198.534810067.03204.0296
10077.99 209.87410082.71212.955910088.95217.2637 10099.9223.962110107.15228.1269
10110.86229.737410121.82 231.421 10131.6233.276610156.05235.261410164.09235.3939
#Mann= 3 , 0 , 0
9888.222    0.04       09888.222    0.04       010164.09    0.04       0
#XS Ineff= 2 , 0
       0                               0
Bank Sta=9888.222,10164.09
Exp/Cntr=0.3,0.1

Type RM Length L Ch R = 1 ,23132.99,176.456900,176.456900,176.456900
XS GIS Cut Line= 6
872406.994113195794776.265103316872376.515203982794724.111337689
872323.909921197794656.621069958872310.012046107794634.376782804
872264.321324442794514.449521746872231.708390532794418.554908767
#Sta/Elev= 30
9799.091241.87399846.603242.3287 9862.01237.80579878.277231.03079883.776229.4112
9896.455224.4511 9910.81219.93689921.813213.48389927.076209.95299943.342201.9317
9958.818191.0042 9970.61183.48619984.985175.93929992.179172.585510003.02171.8608
10013.69172.776310024.37180.286210045.73191.2935 10056.4192.654310067.08197.9196
10077.76202.588310088.43205.387810099.11207.699710109.68213.285810130.81 226.859
10141.37229.286310151.93230.918410173.06235.967410190.77238.927110200.99240.2036
#Mann= 3 , 0 , 0
9799.091    0.12       09799.091    0.12       010200.99    0.12       0
#XS Ineff= 2 , 0
       0                               0
Bank Sta=9799.091,10200.99
Exp/Cntr=0.3,0.1

Type RM Length L Ch R = 1 ,22956.53,176.456800,176.456800,176.456800
XS GIS Cut Line= 6
  872480.0379752794789.810276892872473.469807241  794676.8900022
872474.393277162794590.039942399872474.543689091794588.045606356
872475.783122061794508.077999914872471.281096103794388.170180536
#Sta/Elev= 30
9799.034239.63249823.886239.5247 9843.92240.19149853.937235.92259863.954233.0578
9883.988224.15549894.004221.46949904.021219.44359914.035217.06829924.036 213.133
9934.036208.16449944.037201.96899954.037194.62469964.038188.21319984.039172.8977
 9994.04165.890610004.05164.981410014.05166.690310024.05 170.65810034.05177.1622
10044.05185.569410054.05197.017810064.05207.107510074.05214.827610094.06228.9675
10114.08238.169710124.09242.085510134.09244.405610154.11245.438410200.97245.4823
#Mann= 3 , 0 , 0
9799.034  0.0618       09799.034  0.0618       010200.97  0.0618       0
#XS Ineff= 2 , 0
       0                               0
Bank Sta=9799.034,10200.97
Exp/Cntr=0.3,0.1

Type RM Length L Ch R = 1 ,22780.08,203.773200,203.773200,203.773200
XS GIS Cut Line= 2
872634.252247836 794708.38466067872658.929231009794550.269175894
#Sta/Elev= 21
9908.025218.9806 9911.45218.64949912.874218.31049921.571216.30579931.692212.8195
9941.813 207.5439951.935200.99189962.056191.51419972.177179.32079977.724171.4605
9982.298165.07669992.419159.481810002.54157.237310012.66164.897110022.78173.9183
 10032.9183.440610042.57191.846710043.02192.216810053.15199.558110063.27207.7169
10068.05211.2031
#Mann= 3 , 0 , 0
9908.025    0.12       09908.025    0.12       010068.05    0.12       0
#XS Ineff= 2 , 0
       0                               0
Bank Sta=9908.025,10068.05
Exp/Cntr=0.3,0.1

Type RM Length L Ch R = 1 , 22576.3,203.773200,203.773200,203.773200
XS GIS Cut Line= 6
872741.846169114794848.553046779872801.446674505794774.796829149
872828.253034137794725.669854263872836.903815579794698.808030805
872851.926590919794630.073227111872890.279793218794482.561071272
#Sta/Elev= 30
9799.063198.40919816.829186.12659829.937175.01749834.875171.57259856.154161.5676
9868.762159.23179881.222162.85819905.487173.47659917.277172.46439928.537170.1381
9939.633164.62129950.689155.07889961.194 147.098  9971.7 140.5219982.106136.7036
9992.351136.525610002.59136.817110012.82141.853510023.06149.417510033.29162.4468
10043.52 172.30610064.14187.562310074.47196.559310100.52221.3265 10115.8233.2674
10126.13235.317710167.46235.139310177.79236.655910188.13241.957410200.98249.8081
#Mann= 3 , 0 , 0
9799.063    0.04       09799.063    0.04       010200.98    0.04       0
#XS Ineff= 2 , 0
       0                               0
Bank Sta=9799.063,10200.98
Exp/Cntr=0.3,0.1

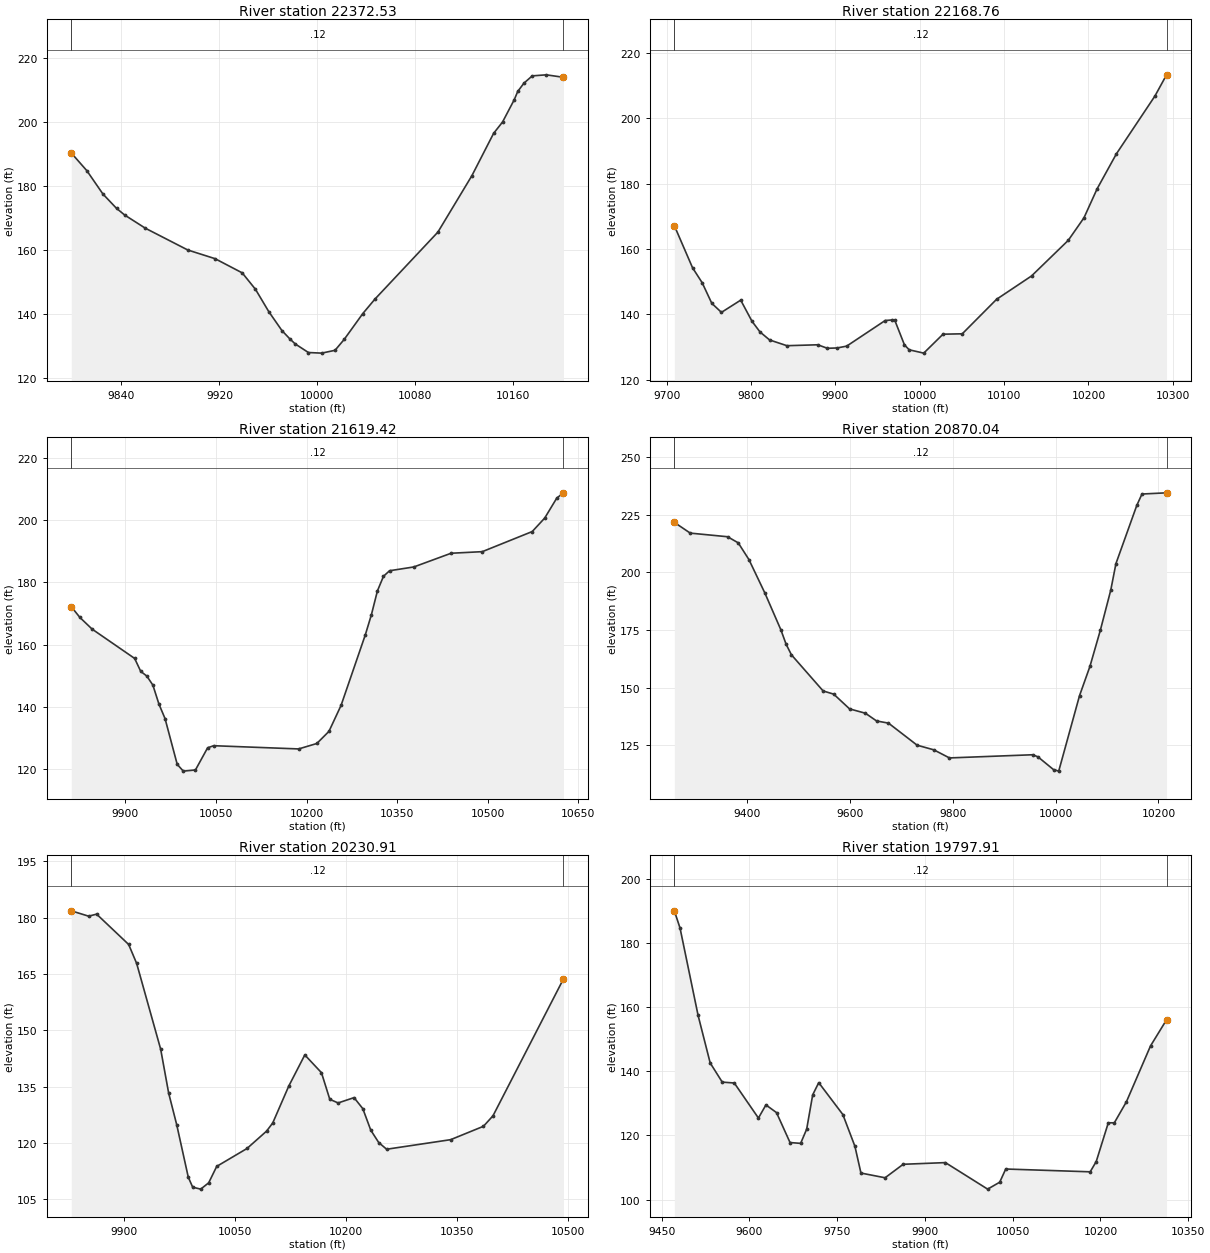
Type RM Length L Ch R = 1 ,22372.53,203.773200,203.773200,203.773200
XS GIS Cut Line= 6
872794.449213484794909.513268201872874.766678698794859.140229636
872991.817142659794807.732169334873030.133262695794785.263915908
873075.623243123794743.649908002873115.393346093794682.736091265
#Sta/Elev= 30
9799.033190.23819811.786184.68319824.871177.40049835.959172.92269842.674170.8164
9859.482166.70719894.158159.88629916.372157.18159938.587152.73559949.419147.5871
9960.222140.63689971.025134.67749977.256132.16569981.828 130.5139992.631 127.815
10003.45127.626910014.36 128.51310021.79131.895910037.07140.022710046.96144.5385
10098.34165.4879 10126.1183.146310143.83196.383910151.11199.921610160.74206.9575
10163.51209.490410168.58212.079710175.36 214.35910186.81214.685810200.86213.9101
#Mann= 3 , 0 , 0
9799.033    0.12       09799.033    0.12       010200.86    0.12       0
#XS Ineff= 2 , 0
       0                               0
Bank Sta=9799.033,10200.86
Exp/Cntr=0.3,0.1

Type RM Length L Ch R = 1 ,22168.76,549.335000,549.335000,549.335000
XS GIS Cut Line= 2
872930.563117826795243.908407377873212.265937504794732.957775823
#Sta/Elev= 30
9709.076167.14929730.668154.26719742.087149.69289753.506143.39179764.925 140.636
9787.763144.37389801.113137.93169810.602134.65989822.021132.20589842.537130.4506
9879.116130.73279890.535 129.6599901.955 129.7619913.374130.3197 9959.05138.1502
9966.809138.31229970.469138.17369981.888130.68539987.521129.195610004.73128.1818
10027.57 133.969 10050.4 134.08710091.08 144.634 10132.5151.764110176.01162.6389
10194.64169.525610210.27178.408810233.11 189.09110278.79206.753910292.54  213.23
#Mann= 3 , 0 , 0
9709.076    0.12       09709.076    0.12       010292.54    0.12       0
#XS Ineff= 2 , 0
       09958.845                       0
Bank Sta=9709.076,10292.54
Exp/Cntr=0.3,0.1

Type RM Length L Ch R = 1 ,21619.42,749.380200,749.380200,749.380200
XS GIS Cut Line= 4
873284.148725973795539.210673522873317.175953108795259.450631911
873342.432067976794966.091143833873282.205947906 794734.90055389
#Sta/Elev= 30
9810.363172.20359824.672168.74599844.811165.02389915.297155.61119925.367151.4676
9935.436149.95679945.506147.04869955.575140.93659965.645136.31239985.784121.6463
9995.853 119.46710015.99119.841510036.13126.9482 10046.2127.620610186.87126.5854
10216.98128.330510237.05132.215110257.12 140.55310297.27163.174410307.31169.6085
10317.35177.297210327.38181.962510337.42183.736210377.57184.949210439.31189.3473
10490.98189.856110573.65196.304710594.31200.625210614.33207.042410625.42208.7248
#Mann= 3 , 0 , 0
9810.363    0.12       09810.363    0.12       010625.42    0.12       0
#XS Ineff= 2 , 0
       0                               0
Bank Sta=9810.363,10625.42
Exp/Cntr=0.3,0.1

Type RM Length L Ch R = 1 ,20870.04,639.126200,639.126200,639.126200
XS GIS Cut Line= 5
873514.517089063795534.852714099873566.600422396795343.880491877
873608.267089063795166.797158544873660.350422396795066.102714099
873729.794866841794607.769380766
#Sta/Elev= 30
9258.935221.77369289.878217.10839362.434215.53379383.165212.87419403.895205.6262
9434.991191.04979466.005175.10959476.278168.78789486.551164.2261 9548.19148.5113
9568.736147.13739599.555140.73079630.374 138.8359652.083135.47929675.223134.5355
9730.893 124.9439763.397 122.926 9793.74119.41229955.566120.7923 9965.68119.8987
9996.023114.335310006.14 113.67610046.59146.471210066.82159.191910087.05174.8905
10107.28192.302910117.39203.873410157.85229.115110167.96234.096610215.73234.6165
#Mann= 3 , 0 , 0
9258.935    0.12       09258.935    0.12       010215.73    0.12       0
#XS Ineff= 2 , 0
       0                               0
Bank Sta=9258.935,10215.73
Exp/Cntr=0.3,0.1

Type RM Length L Ch R = 1 ,20230.91,433.008200,433.008200,433.008200
XS GIS Cut Line= 5
873665.199848144795526.672959826873783.889751991795236.542083758
873816.859169726795172.251719174873858.070941894795065.101111535
873937.197544459794921.684144388
#Sta/Elev= 30
9829.431181.81929852.848180.39649863.652180.9367 9906.87172.86819917.674167.8182
9950.087144.99379960.892133.28759971.696 124.9279987.368110.91169993.305108.2648
10004.11107.752710014.91109.435210025.72113.8011 10066.6118.566810093.01123.1915
10101.35125.366310122.96135.173610144.63143.469210167.11138.738910178.35131.6563
10189.59130.688810211.08132.103310222.92129.163910233.64123.451810244.35120.1597
10255.06118.368510341.49120.9159 10385.7124.4725 10398.6127.265510493.75163.7073
#Mann= 3 , 0 , 0
9829.431    0.12       09829.431    0.12       010493.75    0.12       0
#XS Ineff= 2 , 0
       0                10149.71       0
Bank Sta=9829.431,10493.75
Exp/Cntr=0.3,0.1

Type RM Length L Ch R = 1 ,19797.91,346.166300,346.166300,346.166300
XS GIS Cut Line= 3
874142.989311285795774.436047433 874071.05976274 795486.86678641
873938.128200174794958.463825211
#Sta/Elev= 30
9471.643189.9723 9481.37184.62589512.294157.3573 9532.91142.57639553.526136.6001
9574.143  136.329615.375 125.4069628.201129.49439646.299127.09839669.412117.7685
9687.532117.5129 9697.84121.93549708.148 132.6399718.456136.43399759.688126.4947
9780.308116.5996 9790.62108.26349831.866106.79169862.801110.99479934.982111.5178
10007.16103.253610027.79105.4107 10038.1109.521110182.46108.648310192.77111.8536
 10213.4123.920710223.71123.921210244.33130.460910285.58147.885710312.94156.0176
#Mann= 3 , 0 , 0
9471.643    0.12       09471.643    0.12       010312.94    0.12       0
#XS Ineff= 2 , 0
       0                10083.64       0
Bank Sta=9471.643,10312.94
Exp/Cntr=0.3,0.1

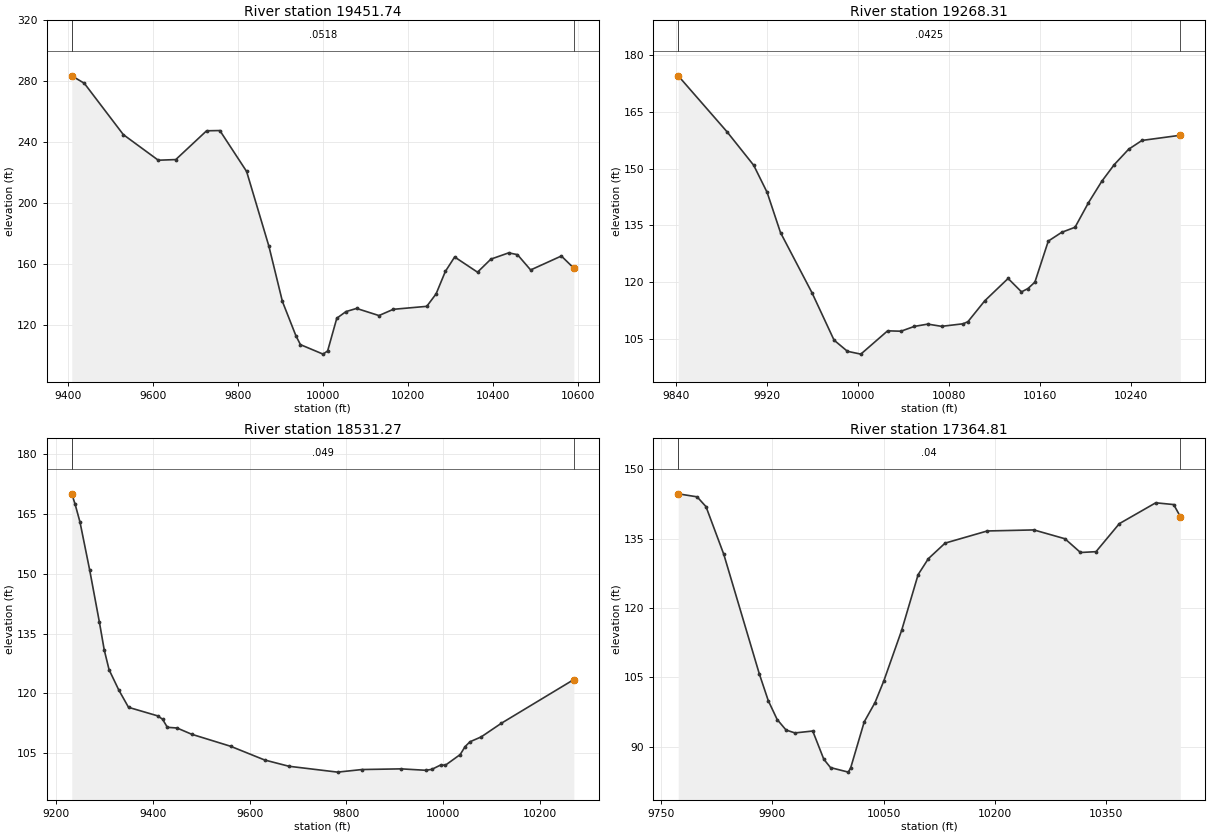
Type RM Length L Ch R = 1 ,19451.74,183.425700,183.425700,183.425700
XS GIS Cut Line= 6
874484.235499582795783.813682558874432.391374915795550.119704102
 874377.78349906795361.460276719 874307.47898186795169.094396262
874185.902237306794916.061153224 874114.19681813794666.572063259
#Sta/Elev= 30
9409.349 283.5099438.769278.63199530.706 244.9139612.908228.12179654.052228.5467
9726.564247.4375 9757.76247.59739820.696220.76029873.203171.62529904.971135.4024
9936.739112.88959947.329107.089510000.57100.859710011.34102.952610032.89124.4194
10054.55128.783310079.46130.849510132.12126.174810165.85130.273310244.55132.2202
10266.51140.399410288.34155.147310310.18164.617810363.97154.636610395.43163.2092
10437.32167.323610457.98166.144810488.96156.102110561.26165.255910590.62157.2615
#Mann= 3 , 0 , 0
9409.349  0.0518       09409.349  0.0518       010590.62  0.0518       0
#XS Ineff= 2 , 0
       0                               0
Bank Sta=9409.349,10590.62
Exp/Cntr=0.3,0.1

Type RM Length L Ch R = 1 ,19268.31,737.044500,737.044500,737.044500
XS GIS Cut Line= 2
874577.017089063795281.380491877874344.378200174794906.380491877
#Sta/Elev= 30
9842.033174.49929884.846159.73329908.382 150.849 9920.15143.69799931.918133.0705
9959.676117.1145 9978.99104.63639990.758101.685410002.53100.939610026.06 107.095
10037.83106.9993 10049.6108.272110061.37108.873210073.49108.285410092.46108.9608
10096.67109.521210111.43115.028110131.97 120.93710143.74117.396210149.37118.2631
10155.51119.965810167.28130.814110179.05133.129310190.81134.475310202.58140.9501
10214.35146.642510225.25151.021610237.89155.091510249.65157.423210283.33158.7896
#Mann= 3 , 0 , 0
9842.033  0.0425       09842.033  0.0425       010283.33  0.0425       0
#XS Ineff= 2 , 0
       0                               0
Bank Sta=9842.033,10283.33
Exp/Cntr=0.3,0.1

Type RM Length L Ch R = 1 ,18531.27,1166.463600,1166.463600,1166.463600
XS GIS Cut Line= 6
874608.964138176795261.885661363874651.803780053794769.229779772
874673.223600992794597.871212262874688.217475649794522.901838977
874671.081618898794422.228680565874525.426836515 794297.99371912
#Sta/Elev= 30
9232.589170.09599239.496167.48529249.527  163.039269.588 150.975 9289.65137.9015
 9299.68130.91259309.711125.93639329.772120.84939349.834116.51839410.018114.3749
9420.049113.54799430.079111.50079450.141111.3295  9480.3109.76049560.736106.7442
9631.044103.30039681.212101.72659781.787100.25529832.176100.90579912.954101.0749
9963.944100.71859976.282100.94189994.441102.031510004.58     10210035.02 104.664
10045.16106.6602 10055.3107.8772 10078.4109.092710120.36 112.53910269.84123.4901
#Mann= 3 , 0 , 0
9232.589   0.049       09232.589   0.049       010269.84   0.049       0
#XS Ineff= 2 , 0
       0                10073.34       0
Bank Sta=9232.589,10269.84
Exp/Cntr=0.3,0.1

Type RM Length L Ch R = 1 ,17364.81,270.351200,270.351200,270.351200
XS GIS Cut Line= 3
875213.003088648795146.218628294875000.946861355794824.921314213
  874915.2675776794546.463642009
#Sta/Elev= 30
9773.332144.72139798.756144.07039810.737141.94539834.701131.61579882.627 105.692
9894.60999.932339906.59195.848239918.57293.573089930.55492.943649954.51793.35671
9969.40187.248049978.48185.4363910002.4484.4547810005.7185.4291210023.8695.34099
10038.3999.5112510050.37104.264710074.33115.180210096.48 127.23210110.28130.6849
10132.79134.044810189.61136.679110252.38136.904810294.23134.992810315.16132.0163
10336.08132.194910367.47138.259510416.55142.779910440.71142.396810449.64139.8021
#Mann= 3 , 0 , 0
9773.332    0.04       09773.332    0.04       010449.64    0.04       0
#XS Ineff= 2 , 0
       0                10063.56       0
Bank Sta=9773.332,10449.64
Exp/Cntr=0.3,0.1