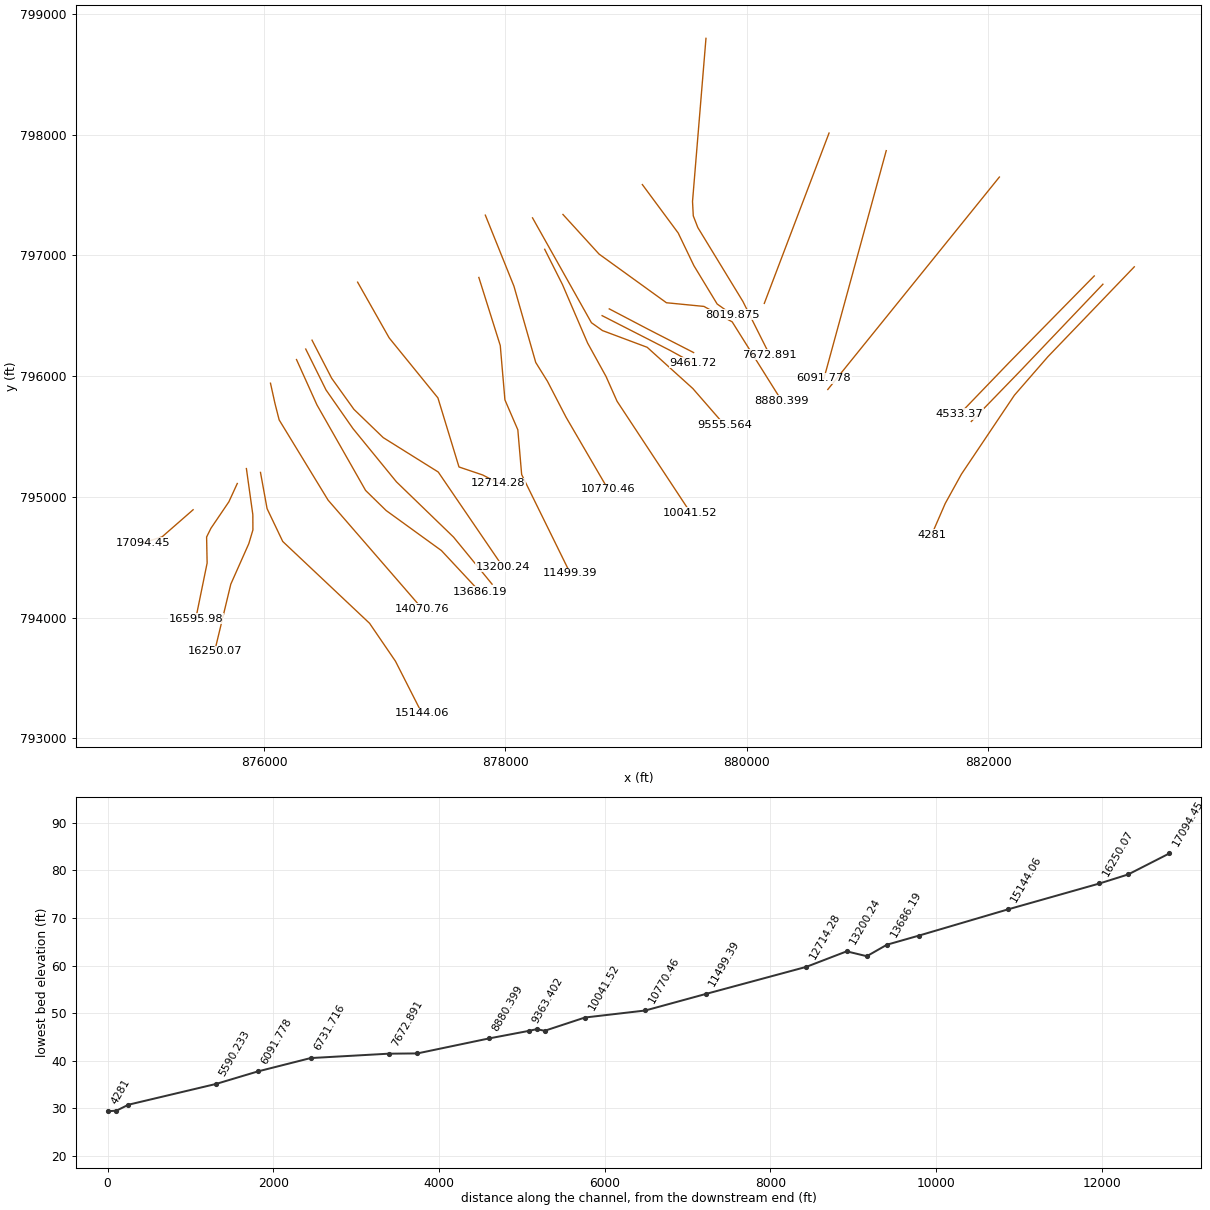
HEC-RAS study 11856_ras.prj: 11856

--- 11856_ras.g01 (geometry) --- (continued)

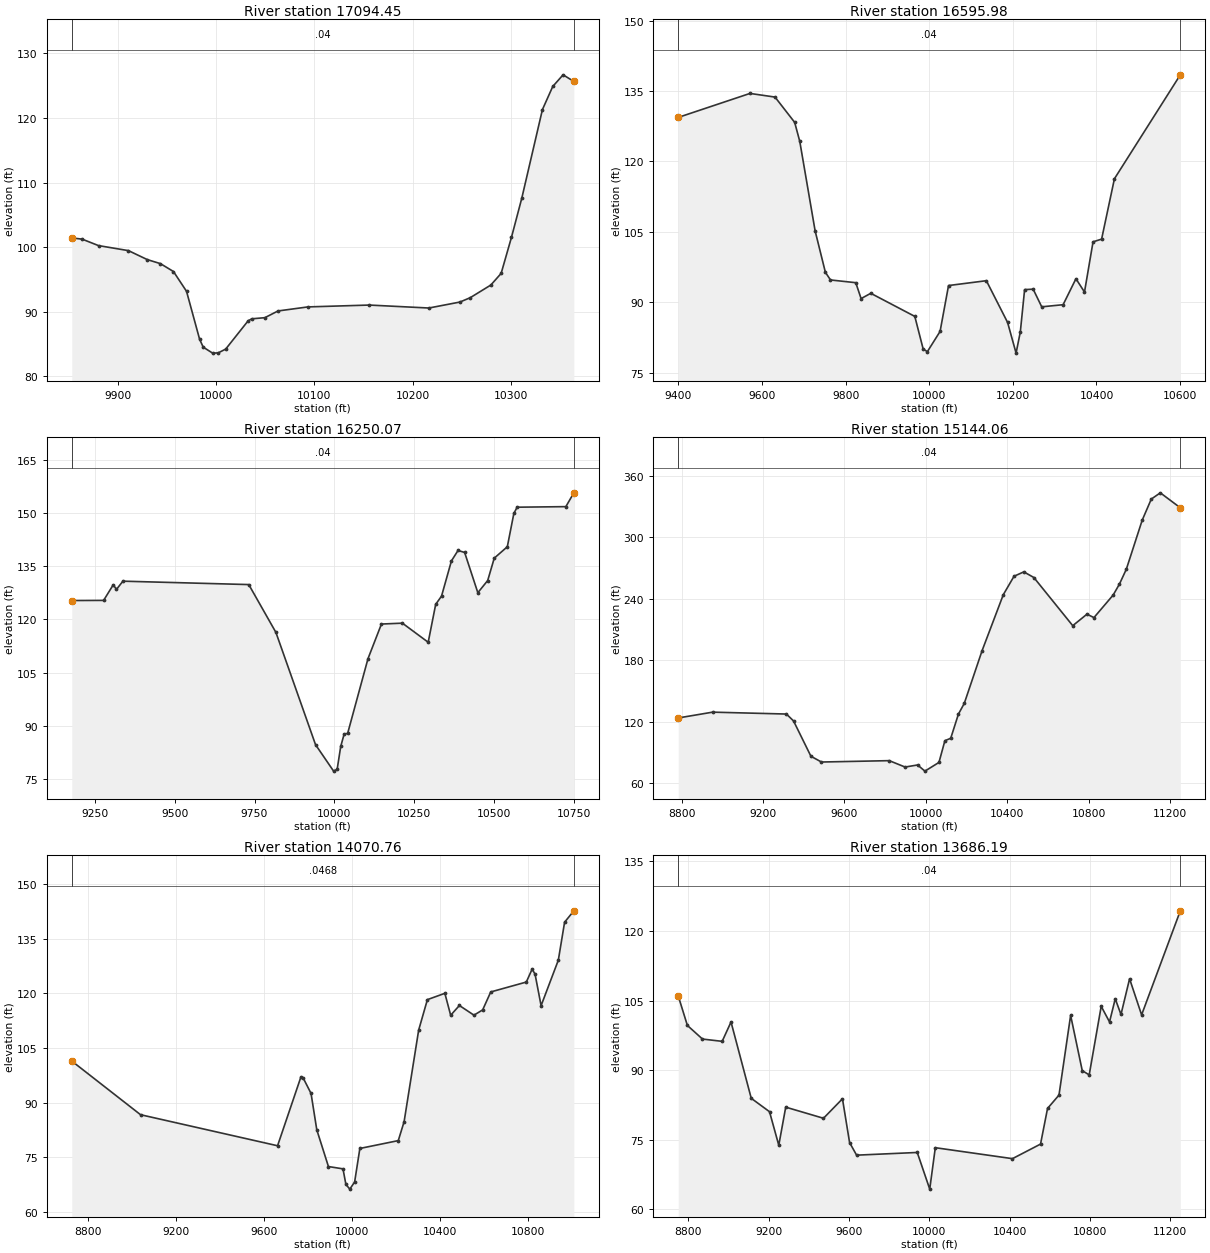
Type RM Length L Ch R = 1 ,17094.45,498.477300,498.477300,498.477300
XS GIS Cut Line= 3
875412.909624051794892.885034744875155.831632598794668.526060385
874994.573619778794617.110462095
#Sta/Elev= 30
9853.432101.4116 9863.93101.22839880.632100.22539911.04999.446939930.29498.05026
9943.56797.431519956.83996.206539970.112 93.13959983.38585.72096 9987.0984.48383
9996.65783.55957 10002.383.5963710009.9384.1864110032.7288.5627110036.4888.87811
10049.7589.0533410063.1390.0957710093.5590.7227110155.9391.0096210216.5190.55087
   1024891.4746410258.4992.1467810279.49  94.11110289.9895.9184410300.48101.5062
10310.97107.571310331.97121.312810342.46124.891110352.96 126.694 10363.9125.6701
#Mann= 3 , 0 , 0
9853.432    0.04       09853.432    0.04       0 10363.9    0.04       0
#XS Ineff= 2 , 0
       0                10225.85       0
Bank Sta=9853.432,10363.9
Exp/Cntr=0.3,0.1

Type RM Length L Ch R = 1 ,16595.98,345.905300,345.905300,345.905300
XS GIS Cut Line= 6
875778.998991973795110.504765784875709.453993712794959.004238726
875560.595375568794739.384618292875524.709446811794666.985796644
875529.056232884794451.423682694875434.967401573793990.509143124
#Sta/Elev= 30
9399.563 129.3939571.203134.50789631.102133.72879678.068 128.3389690.312124.2655
9727.044105.18279751.53296.370569763.776 94.73429824.23794.151549836.95490.76111
9860.14391.888819965.44886.963529985.50979.986429995.55779.45436 10025.9 83.7564
10046.1393.54302 10136.694.5755310187.3885.6786710207.6979.1315810217.8683.67279
10228.0992.6753810248.5692.7687310269.0289.0053110320.18 89.456110350.8894.99427
10371.3492.15455 10391.8102.862510412.27  103.4410442.96116.316610600.54138.4742
#Mann= 3 , 0 , 0
9399.563    0.04       09399.563    0.04       010600.54    0.04       0
#XS Ineff= 2 , 0
       0                10114.73       0
Bank Sta=9399.563,10600.54
Exp/Cntr=0.3,0.1

Type RM Length L Ch R = 1 ,16250.07,1106.007800,1106.007800,1106.007800
XS GIS Cut Line= 6
875854.431005333795234.174424504875907.805745967794851.892776621
875908.444037372794725.761083062875874.548187301794612.265794971
875725.127647674794276.102363353875591.449088236793720.361965901
#Sta/Elev= 30
9177.658125.32329277.424125.36239307.603129.76769317.662 128.4649337.868130.7796
9731.997129.8198 9817.03116.33229941.08684.695749997.70277.2367110008.8377.74254
10019.97 84.188110030.8587.7244610041.5887.8445210105.42108.940510147.53 118.697
10213.15118.944810293.96113.559510317.41124.246810335.72 126.56910366.72136.4931
10387.39139.434910408.06138.8723 10449.4127.529110480.32130.9675 10500.8137.2642
10541.74140.480810562.22149.875610572.45151.630710725.08151.7889 10750.1155.6818
#Mann= 3 , 0 , 0
9177.658    0.04       09177.658    0.04       0 10750.1    0.04       0
#XS Ineff= 2 , 0
       0                               0
Bank Sta=9177.658,10750.1
Exp/Cntr=0.3,0.1

Type RM Length L Ch R = 1 ,15144.06,1073.306100,1073.306100,1073.306100
XS GIS Cut Line= 6
875971.218073678795202.331534791876025.781111725794902.245125458
876155.554659866  794630.1277094876875.067186222 793952.03816375
877089.883014708 793637.43186654877309.313970135793205.664900191
#Sta/Elev= 30
8783.947123.6677 8952.95129.34129315.475127.49599350.484120.76729435.95286.29041
9487.61380.676319820.87782.009189898.55175.770079960.00577.790519996.06171.78588
10065.0580.2835510094.17101.467110122.89103.8615 10160.8127.499310189.38137.8584
10277.13 189.44510381.24243.983310433.93261.960110482.06266.2305 10531.3 260.722
10722.41213.715710792.16 224.93110826.66221.621710921.14 243.65210951.82254.2922
10985.75268.837211063.85316.753611108.39337.282711152.74 343.36211250.94328.7654
#Mann= 3 , 0 , 0
8783.947    0.04       08783.947    0.04       011250.94    0.04       0
#XS Ineff= 2 , 0
       09746.311                       0
Bank Sta=8783.947,11250.94
Exp/Cntr=0.3,0.1

Type RM Length L Ch R = 1 ,14070.76,384.563500,384.563500,384.563500
XS GIS Cut Line= 6
876054.069571491795941.430478901876091.515228089795772.259413413
876126.026981852795637.121300732876531.287504246794972.682537273
876906.287504246794540.390870606877312.537504246794071.640870606
#Sta/Elev= 30
8726.846101.40549039.587 86.69039662.87678.176049768.296 96.90019780.00996.68292
9815.14992.521619841.27282.549529894.22572.474199960.41671.841249973.65467.58489
9991.39766.2833710013.3768.2371110037.1877.4344510211.9479.5868910238.4284.77704
10304.61109.881710344.32118.241610423.74119.975910450.21113.963210489.91116.6374
10556.13113.984210595.77115.434210632.48120.352110794.26123.064810820.73126.6166
10833.96125.245610861.51116.591910939.83129.060410968.39139.478411010.44142.5948
#Mann= 3 , 0 , 0
8726.846  0.0468       08726.846  0.0468       011010.44  0.0468       0
#XS Ineff= 2 , 0
       09806.339        10109.39       0
Bank Sta=8726.846,11010.44
Exp/Cntr=0.3,0.1

Type RM Length L Ch R = 1 ,13686.19,242.978200,242.978200,242.978200
XS GIS Cut Line= 6
876269.689253887796137.432816728876438.848415879795761.936698046
876842.205047593795052.826015424 877012.37808809794886.475362374
877470.552020494794554.708009274877789.512667537 794212.60494897
#Sta/Elev= 30
8749.094106.00528794.721 99.63748869.99196.706158967.99996.215169012.145100.3853
9112.88583.943989203.89981.056159250.07873.830149284.71282.036969472.86679.64096
9567.45283.837639602.91674.409819637.87471.693389940.10172.2738210002.3164.37467
10030.0773.3007710414.4370.9396510554.4174.0774510589.3281.7596210646.3484.63213
10704.35101.811410762.2889.9019510796.8988.9873810856.73103.758810898.18 100.399
10926.71105.382410955.25102.000210998.13109.695311058.03101.913811250.91 124.335
#Mann= 3 , 0 , 0
8749.094    0.04       08749.094    0.04       011250.91    0.04       0
#XS Ineff= 2 , 0
       09794.423        10082.62       0
Bank Sta=8749.094,11250.91
Exp/Cntr=0.3,0.1

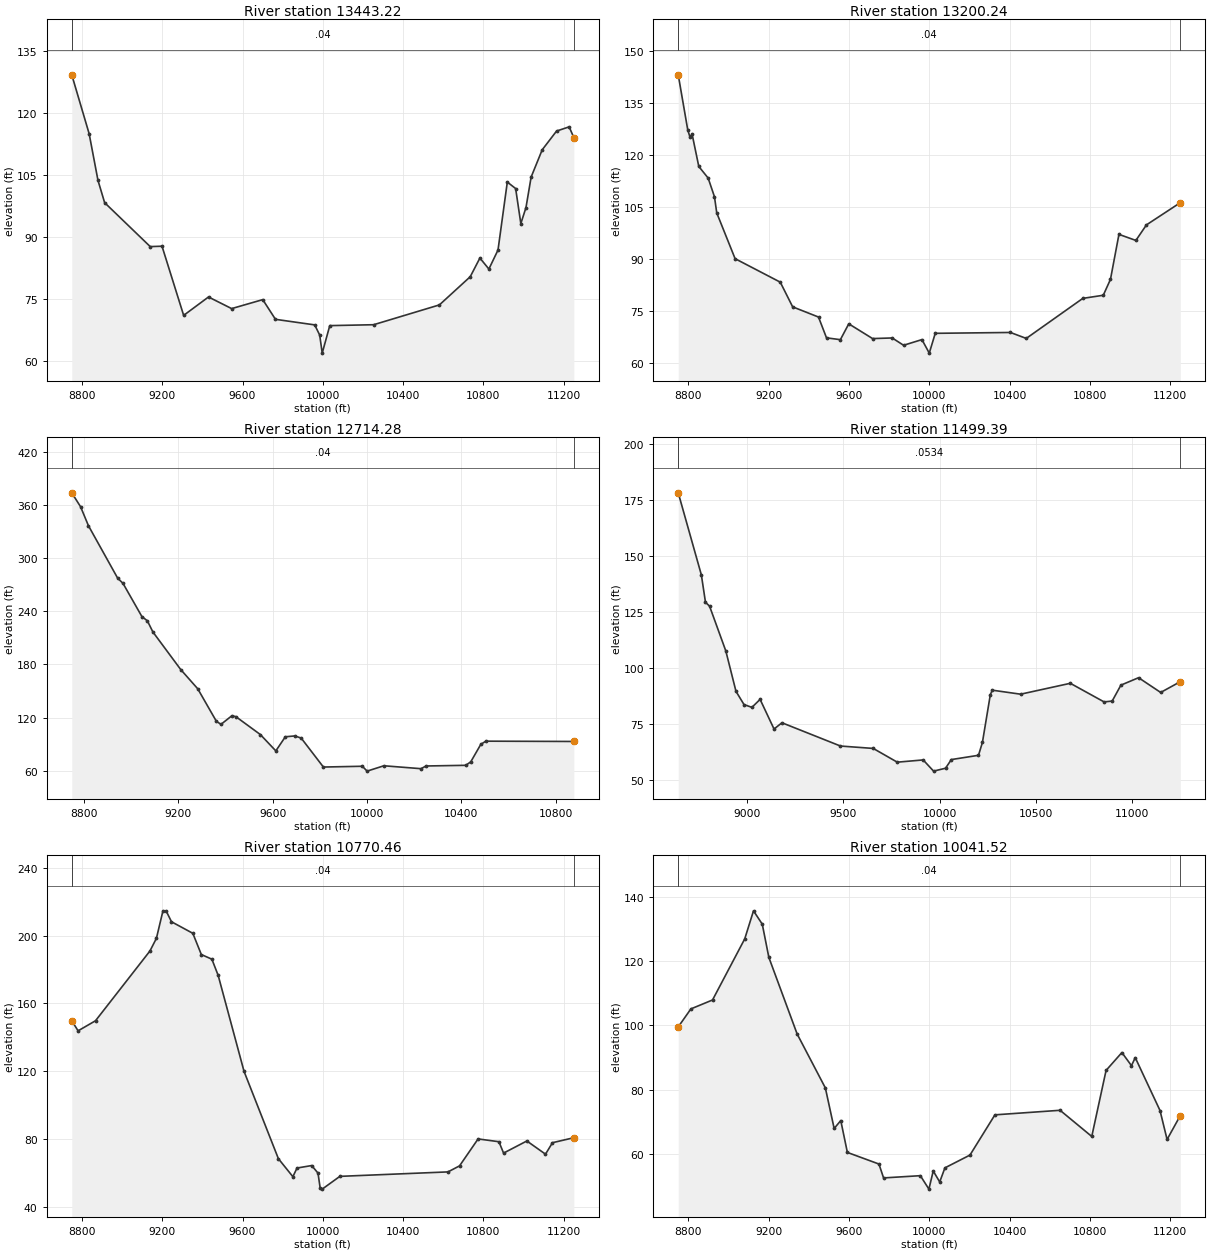
Type RM Length L Ch R = 1 ,13443.22,242.978300,242.978300,242.978300
XS GIS Cut Line= 6
 876346.16976885796224.435385141876514.199232648795885.638805714
876737.528185162 795565.42873306877097.289542068795124.637167526
877570.749286757794666.405772656877890.249605255794276.347962791
#Sta/Elev= 30
8749.044 129.2418835.593 115.0098879.617103.72718912.78298.33617 9139.9787.71332
9198.72487.806069306.59371.084579430.40675.532589545.80372.723749700.73574.89265
9764.11770.129499959.68368.786059984.58566.313149997.037  61.95910034.7268.60862
10253.2168.8267610580.9673.6156810734.6280.4302710782.7684.9428110827.6282.29177
10873.0886.8955110919.41103.316410960.92101.748610986.7893.2786811012.4497.15367
11038.11104.521711093.26111.115611164.84 115.64711227.56116.663511250.95114.0538
#Mann= 3 , 0 , 0
8749.044    0.04       08749.044    0.04       011250.95    0.04       0
#XS Ineff= 2 , 0
       09719.666        10082.37       0
Bank Sta=8749.044,11250.95
Exp/Cntr=0.3,0.1

Type RM Length L Ch R = 1 ,13200.24,485.956500,485.956500,485.956500
XS GIS Cut Line= 6
876398.139028244796298.110606372876561.097740177795982.222541212
876744.864522596795725.484091315876988.244244914795490.601424834
877444.010919154795205.610421462877979.186338877794421.249362335
#Sta/Elev= 30
8749.107143.18248796.339127.37388807.295125.2855 8818.25126.06118851.529116.7781
8898.155113.42718929.708108.03538940.971103.3946 9032.4790.198239257.52183.43132
9319.27976.314669448.03473.37971  9487.9 67.38639557.00266.857569598.89571.42366
9717.52167.172959815.35767.353079871.96665.245789963.43366.878849999.99762.98076
10029.7768.6879210404.3368.9352410483.2967.2188310765.1478.7589710867.0679.66046
 10902.984.2437410945.1397.2052811029.4895.4581511082.1299.9356311250.91106.3428
#Mann= 3 , 0 , 0
8749.107    0.04       08749.107    0.04       011250.91    0.04       0
#XS Ineff= 2 , 0
       09663.698         10217.9       0
Bank Sta=8749.107,11250.91
Exp/Cntr=0.3,0.1

Type RM Length L Ch R = 1 ,12714.28,1214.891400,1214.891400,1214.891400
XS GIS Cut Line= 6
876776.090114509796778.687706476877037.685292454796316.671296728
 877441.48799434795819.619254205877616.050708615795247.350810603
877812.537504246795181.015870606 877942.74583758795113.307537273
#Sta/Elev= 30
8749.141373.47898786.494357.77578819.758336.40748943.421277.34178966.257 271.379
9046.184234.00529069.381229.19969092.784216.63669210.689174.26949282.749152.6046
9361.892115.8695 9381.45112.47399427.596122.19569444.775121.06679548.107100.9578
9613.71582.547679654.00598.464469694.29599.391919721.15696.965959815.16664.33314
9980.28665.2170210000.4259.7257610071.4765.7638610228.9262.47781   1025065.52267
10418.5866.2806210439.6670.2517510482.0889.8953510503.3693.4979510876.2993.16286
#Mann= 3 , 0 , 0
8749.141    0.04       08749.141    0.04       010876.29    0.04       0
#XS Ineff= 2 , 0
       0                 10514.4       0
Bank Sta=8749.141,10876.29
Exp/Cntr=0.3,0.1

Type RM Length L Ch R = 1 ,11499.39,728.934800,728.934800,728.934800
XS GIS Cut Line= 6
877780.578229154796817.644999735877958.050741272796253.666529774
877996.596866649795803.351395996878103.586936647795555.360843836
878135.263144069795184.769109456878537.910885444794366.088717449
#Sta/Elev= 30
8642.296178.2687 8762.47  141.628783.807129.41928805.144127.65128889.593107.6496
8942.33189.644948984.18383.715349025.13382.496769067.58986.058429139.99872.82053
9181.20375.61244  9485.365.221589655.44264.154829780.23758.019129914.92759.01911
9968.95954.0210510031.0755.3155410061.2159.1801810202.3461.0901710222.6966.82518
 10263.988.1981510274.21 90.156710421.23 88.369410679.3893.2318510854.8284.92448
10896.7985.2947310942.2392.4130411034.0695.7312111148.8389.1472511250.8893.95677
#Mann= 3 , 0 , 0
8642.296  0.0534       08642.296  0.0534       011250.88  0.0534       0
#XS Ineff= 2 , 0
       0                               0
Bank Sta=8642.296,11250.88
Exp/Cntr=0.3,0.1

Type RM Length L Ch R = 1 ,10770.46,728.934800,728.934800,728.934800
XS GIS Cut Line= 6
 877834.40111066797334.008517027878071.461406274796745.036591814
878251.993902714 796113.30028931878349.497029632 795956.59432174
878502.565620006795660.719038135878850.758481928 795063.31114512
#Sta/Elev= 30
8749.051149.84918780.536143.86458867.365149.81119138.627190.93569170.852198.4042
9203.076214.42069218.982214.60639245.987208.15679352.257201.35649394.648188.8399
9447.202186.09989478.621176.53519607.502119.95959778.64268.502199850.84657.88644
9871.47562.989149944.56764.452679975.99760.003349986.47451.50037 9996.9550.55152
10084.9458.0779810623.72 60.706210681.4364.2695810773.7680.1456810877.6378.49709
10900.7271.7836111016.74 78.938211109.6271.1556711144.4577.92007 11250.980.86092
#Mann= 3 , 0 , 0
8749.051    0.04       08749.051    0.04       0 11250.9    0.04       0
#XS Ineff= 2 , 0
       09921.829                       0
Bank Sta=8749.051,11250.9
Exp/Cntr=0.3,0.1

Type RM Length L Ch R = 1 ,10041.52,485.956500,485.956500,485.956500
XS GIS Cut Line= 6
878326.303178531797050.975741631878473.665555706 796758.36255726
878681.616110125796274.511478401878834.417903224  795997.3593143
878925.630706178795792.225959891879534.126566367794868.896699706
#Sta/Elev= 30
8749.09699.544158812.158105.14798919.975107.92419080.429126.92729124.141135.6617
9167.854131.51259200.638121.1749 9341.5997.344589482.19980.564559526.07367.94571
9559.00870.410059591.94260.494549749.20656.88234  9772.352.56123 9955.5453.25954
 9998.2549.0755610019.7354.7225310052.0851.3028210077.9155.6907810202.8559.67317
10327.1372.1864410651.8573.60358 10809.765.4644310881.0686.0126710959.8591.56866
11007.5987.4905711026.3889.9927211149.7973.5382811185.0464.5255411250.9571.97154
#Mann= 3 , 0 , 0
8749.096    0.04       08749.096    0.04       011250.95    0.04       0
#XS Ineff= 2 , 0
       09557.778                       0
Bank Sta=8749.096,11250.95
Exp/Cntr=0.3,0.1

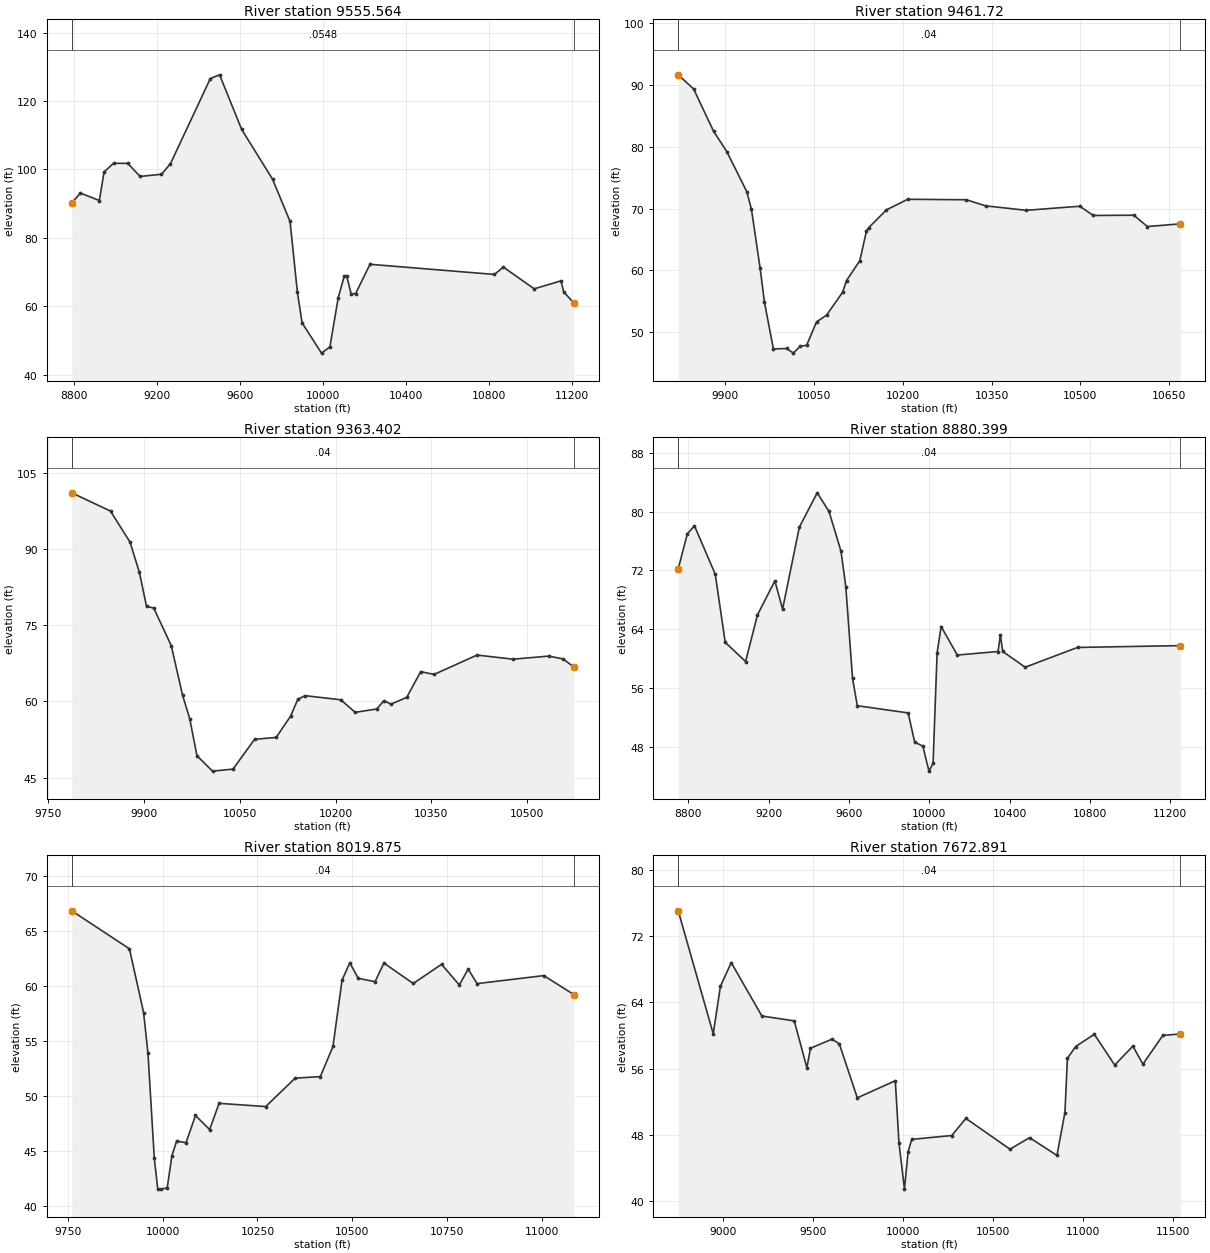
Type RM Length L Ch R = 1 ,9555.564,93.844500,93.844500,93.844500
XS GIS Cut Line= 6
878225.381061304797311.429747288878713.358322561796442.803783374
878805.116773153796377.540475289879175.488863035796239.008932058
879553.606347732795897.420873279879815.595083869795596.531575685
#Sta/Elev= 30
 8789.1290.226268830.76293.062468922.20790.906668945.06999.269438990.792101.7893
9059.376101.76099118.62297.941459221.83898.575299265.113101.65249457.492126.5724
9502.032127.64879608.692 111.6789757.57497.13571 9842.0584.777279877.32264.14795
9899.91755.156869993.72246.2850110034.2348.1074110074.51 62.510710103.2668.75786
10115.5468.7910410136.7863.5794510158.5363.7170510227.6472.2557210828.09 69.2881
10870.4971.4501111019.5165.0856311149.1267.4116911161.8764.17528 11210.960.95765
#Mann= 3 , 0 , 0
 8789.12  0.0548       0 8789.12  0.0548       0 11210.9  0.0548       0
#XS Ineff= 2 , 0
       09936.422        10095.08       0
Bank Sta=8789.12,11210.9
Exp/Cntr=0.3,0.1

Type RM Length L Ch R = 1 , 9461.72,98.317900,98.317900,98.317900
XS GIS Cut Line= 4
878801.922655894796501.244844269879162.250342984796317.181350431
879363.472298112796214.230582691 879553.77523242796109.719954834
#Sta/Elev= 30
9820.93391.600059846.84789.321639880.53482.496389902.99279.19485 9936.6872.71439
9944.573 69.85879959.13860.387739966.55654.833079981.59747.3099810004.0547.38419
10015.2846.6362610026.5147.7151710037.7447.9113210054.49 51.680810071.4352.77787
10098.4556.4663110105.1258.3692810127.5861.57914 10138.866.3875910142.4266.88884
10172.4969.7798110208.3671.4917610307.2771.4168210340.1170.4275510408.3669.71253
10498.9670.3692810521.7768.8770110590.2368.9199310613.0567.0889710668.69 67.5237
#Mann= 3 , 0 , 0
9820.933    0.04       09820.933    0.04       010668.69    0.04       0
#XS Ineff= 2 , 0
       09931.109        10140.79       0
Bank Sta=9820.933,10668.69
Exp/Cntr=0.3,0.1

Type RM Length L Ch R = 1 ,9363.402,483.003200,483.003200,483.003200
XS GIS Cut Line= 3
878861.197340351796557.399808491879185.648244743796387.375055708
879560.014672889796195.512261284
#Sta/Elev= 30
9786.549101.14689847.29297.543959877.895 91.41819892.45185.497089903.74178.76124
9915.03178.424669942.52770.999719960.19161.23677 9971.4856.58457 9982.7749.28733
10007.1646.2641210039.2246.6603310073.09 52.534810106.9652.9156210129.5457.10016
10140.8360.4204110152.1261.1491110208.3160.3303910230.78 57.859110264.4958.52101
10275.7360.1333710286.9659.4790910311.5460.8005310333.4665.8854810354.3865.33012
10421.8169.1541210477.9968.3406510534.1768.9481810556.6568.3903810573.5266.79928
#Mann= 3 , 0 , 0
9786.549    0.04       09786.549    0.04       010573.52    0.04       0
#XS Ineff= 2 , 0
       0                10158.05       0
Bank Sta=9786.549,10573.52
Exp/Cntr=0.3,0.1

Type RM Length L Ch R = 1 ,8880.399,860.523300,860.523300,860.523300
XS GIS Cut Line= 6
878477.547898603797339.577244287 878776.63139353797011.477705439
879334.941068497796608.240558369879645.330574642796577.832810875
879879.730014059796449.827294461880291.443992865795793.512912039
#Sta/Elev= 30
8749.27572.220568794.90976.993568830.11778.068058933.73871.473028983.35162.20088
9084.84559.592249143.98965.931169230.714 70.57399269.17666.733879352.70677.88604
9441.70382.55901 9500.5380.017189560.29474.60213  9584.269.786669617.66157.28619
9641.47253.575459894.76452.593959927.52948.605549967.98148.079579998.53144.66925
10018.8845.7266610039.1260.7737610059.1364.35774 10139.760.4743710342.6660.95557
10354.2663.2120910365.8760.9587910477.8858.8193110738.8861.50901 11250.8 61.7557
#Mann= 3 , 0 , 0
8749.275    0.04       08749.275    0.04       0 11250.8    0.04       0
#XS Ineff= 2 , 0
       0                               0
Bank Sta=8749.275,11250.8
Exp/Cntr=0.3,0.1

Type RM Length L Ch R = 1 ,8019.875,346.984600,346.984600,346.984600
XS GIS Cut Line= 5
879135.454170913797587.265870606879432.329170913797186.224203939
879562.537504246796915.390870606 879755.24583758796597.682537273
 879880.24583758796509.140870606
#Sta/Elev= 30
9760.30566.850689912.42663.396469949.75157.59274 9961.2353.918799978.03744.32064
9987.07641.554779994.84441.5330310011.9641.63566 10024.444.5686810036.8445.90195
10061.7345.7612410086.6148.2323710123.94 46.949710148.8249.3387710271.7349.04486
 10349.451.6257910415.9751.7724410449.2654.5153510473.1560.5432410493.6462.12553
10515.8360.7096110560.2460.4052910583.6362.0961610660.9460.2414910735.6761.98485
10782.4660.1096310805.8561.5477810829.2460.2302511005.2160.9566811084.5559.23556
#Mann= 3 , 0 , 0
9760.305    0.04       09760.305    0.04       011084.55    0.04       0
#XS Ineff= 2 , 0
       09817.302                       0
Bank Sta=9760.305,11084.55
Exp/Cntr=0.3,0.1

Type RM Length L Ch R = 1 ,7672.891,941.174800,941.174800,941.174800
XS GIS Cut Line= 6
879662.548962128798799.127446422879551.105324444797447.571546084
879557.459006523797327.868728582879595.281911441797230.907274672
879968.104942511796619.738281268880189.861777975796177.109464065
#Sta/Elev= 30
8749.029 75.03678943.65660.206028983.759 65.93759043.89268.792959214.18562.35262
9394.49461.763689464.61556.114949484.64958.464989604.86359.564949644.96359.00409
9745.21252.485059956.56854.54532 9976.86 47.062910007.4241.47596 10027.846.00856
10048.18 47.4775 10270.8 47.940710349.1350.00667 10594.546.2901810703.2747.68324
10855.6845.5399610900.19 50.713310913.9357.2553110959.5958.6661611063.5360.15475
11176.99 56.437111278.12 58.722611333.8256.54699 11444.960.0174811541.9660.18378
#Mann= 3 , 0 , 0
8749.029    0.04       08749.029    0.04       011541.96    0.04       0
#XS Ineff= 2 , 0
       09913.274                       0
Bank Sta=8749.029,11541.96
Exp/Cntr=0.3,0.1

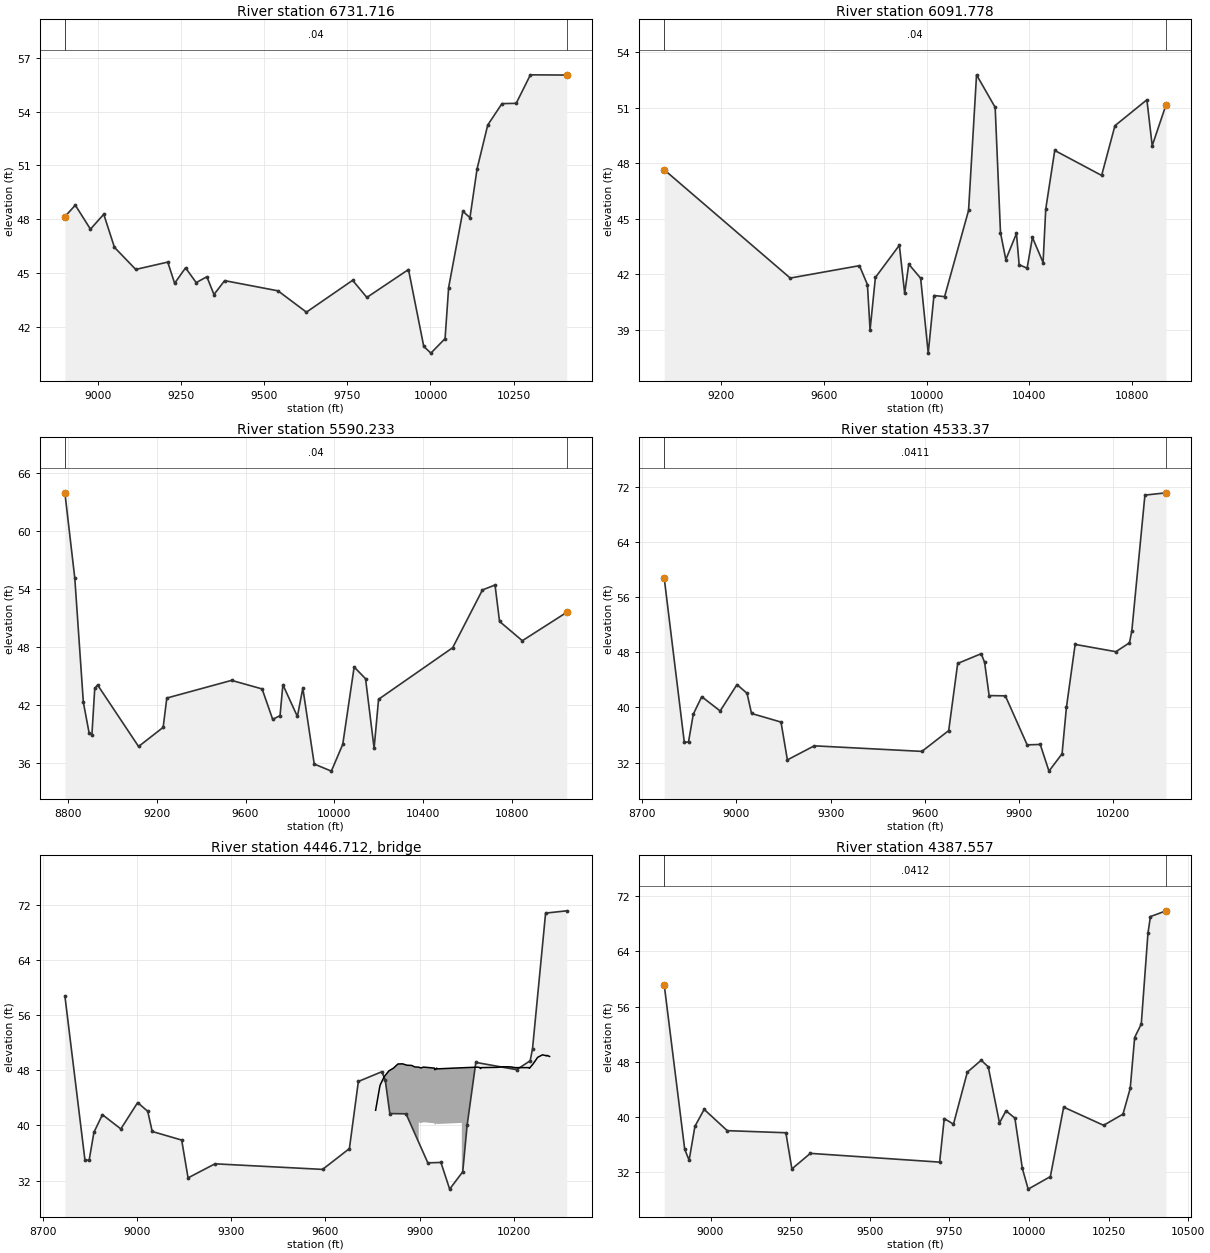
Type RM Length L Ch R = 1 ,6731.716,639.937500,639.937500,639.937500
XS GIS Cut Line= 2
880682.329170913798014.349203939 880145.87083758796602.890870606
#Sta/Elev= 30
8899.88548.152028931.28348.791288976.80847.454289016.86648.28501 9048.9646.44505
9113.14745.213369209.42945.622559230.13144.442449262.91845.302689295.01244.48135
9327.10644.805939348.50243.817549380.59544.589869541.06444.023069626.64842.83595
9765.72144.609069808.51243.655239933.80545.209039979.67940.9329810001.0840.55538
10043.8741.3636710054.5644.2047410097.3648.4515810118.7548.0961910140.1550.80991
10172.2453.2510310215.0354.4420410257.8354.4576410300.6256.0446510409.8556.03176
#Mann= 3 , 0 , 0
8899.885    0.04       08899.885    0.04       010409.85    0.04       0
#XS Ineff= 2 , 0
       09526.525                       0
Bank Sta=8899.885,10409.85
Exp/Cntr=0.3,0.1

Type RM Length L Ch R = 1 ,6091.778,501.545400,501.545400,501.545400
XS GIS Cut Line= 2
881156.287504246797868.515870606880640.662504246795983.099203939
#Sta/Elev= 30
8977.49147.645939468.39641.791889737.94342.461499769.04541.440329779.41238.98969
9800.14641.823729893.45143.565299914.18640.961049930.08242.543149976.38941.78315
 10005.937.7341510028.2340.8485210069.6940.78784   1016345.44473 10194.152.77677
10266.6751.0172810287.4144.2387210308.14 42.790310349.6144.2002510359.9842.51446
10391.0842.3247210411.81 43.987610453.2842.6317710463.6545.5220310498.7148.68859
10681.3647.33898 10733.250.02764 10857.651.4272410878.3448.9441710932.1451.15625
#Mann= 3 , 0 , 0
8977.491    0.04       08977.491    0.04       010932.14    0.04       0
#XS Ineff= 2 , 0
       09472.363                       0
Bank Sta=8977.491,10932.14
Exp/Cntr=0.3,0.1

Type RM Length L Ch R = 1 ,5590.233,1056.862900,1056.862900,1056.862900
XS GIS Cut Line= 2
882093.787504246797649.765870606880671.912504246795889.349203939
#Sta/Elev= 30
8785.52263.957258830.21255.115378868.77542.264078894.484 39.11178907.33838.85863
8920.19343.695128933.04744.046239117.80837.670189228.69939.653399245.12842.69064
9537.20644.522589674.83443.635679722.57940.483419755.73240.867419768.58644.07045
9833.98440.779769858.56743.721589909.98535.851599987.11235.1176110038.5337.89333
10089.95   45.9110141.3644.6921110179.9337.4870810200.03 42.562610534.2547.90843
 10668.4 53.889910725.23 54.407610745.5250.6341910848.3648.6314711048.4451.57098
#Mann= 3 , 0 , 0
8785.522    0.04       08785.522    0.04       011048.44    0.04       0
#XS Ineff= 2 , 0
       09210.162                       0
Bank Sta=8785.522,11048.44
Exp/Cntr=0.3,0.1

Type RM Length L Ch R = 1 , 4533.37,145.813400,145.813400,145.813400
XS GIS Cut Line= 3
882879.874724835796830.221197862882172.520736231796110.402821794
881764.312046772795686.613648005
#Sta/Elev= 30
8770.30658.79369 8834.3334.926728847.72834.989948862.86539.009618889.78841.55703
8948.46839.48595 9001.9543.310769034.07242.044549048.339 39.11819142.15237.87169
9162.47832.385329248.08134.42576  9590.833.61718  9676.136.637329704.63446.37542
9779.50847.789849790.34946.535519804.76341.714629856.43341.675239925.856 34.5649
9967.50934.625959995.27930.7542910036.9333.2695910050.8239.9891410078.5949.13903
10208.3748.0811210251.6149.3723110259.0951.1164910300.7470.7974110367.9271.12782
#Mann= 3 , 0 , 0
8770.306  0.0411       08770.306  0.0411       010367.92  0.0411       0
#XS Ineff= 2 , 0
       0                10093.23       0
Bank Sta=8770.306,10367.92
Exp/Cntr=0.3,0.1

Type RM Length L Ch R = 3 ,4446.712,,,
BEGIN DESCRIPTION:
END DESCRIPTION:
Bridge Culvert--1,0,-1,-1, 0
Deck Dist Width WeirC Skew NumUp NumDn MinLoCord MaxHiCord MaxSubmerge Is_Ogee
61.586700,22.640000,2.6,0, 37, 37, , , 0.95, 0, 0,0,,
 9759.56 9772.54 9774.19 9787.07 9801.75 9816.14 9830.66 9845.18 9859.70 9874.23
 9884.49 9896.92 9896.92 9903.27 9912.07 9946.84 9948.06 9954.20 9954.4010034.06
10034.0610083.9410089.4410094.2210095.6410146.3010165.3810189.3410203.6810246.71
10249.0710261.0610275.4010290.9110304.0910304.8610313.37
   42.20   45.55   45.87   47.08   47.91   48.30   48.91   48.93   48.73   48.70
   48.48   48.45   48.45   48.33   48.46   48.31   48.07   48.31   48.20   48.36
   48.36   48.45   48.41   48.24   48.38   48.42   48.51   48.49   48.38   48.38
   48.28   48.93   49.87   50.24   50.09   50.16   50.00
 -957.80 -954.45 -954.13 -952.92 -952.09 -951.70 -951.09 -951.07 -951.27 -951.30
 -951.52 -951.55   40.45   40.33   40.46   40.31   40.07   40.31   40.20   40.36
 -951.64 -951.55 -951.59 -951.76 -951.62 -951.58 -951.49 -951.51 -951.62 -951.62
 -951.72 -951.07 -950.13 -949.76 -949.91 -949.84 -950.00
 9759.56 9772.54 9774.19 9787.07 9801.75 9816.14 9830.66 9843.12 9859.70 9870.70
 9884.49 9898.28 9903.27 9912.07 9946.84 9948.06 9954.20 9954.40 9966.70 9966.70
10083.9410089.4410094.2210095.6410103.8410103.8410165.3810189.3410203.6810246.71
10249.0710261.0610275.4010290.9110304.0910304.8610313.37
   42.20   45.55   45.87   47.08   47.91   48.30   48.91   48.94   48.73   48.73
   48.48   48.44   48.33   48.46   48.31   48.07   48.31   48.20   48.23   48.23
   48.45   48.41   48.24   48.38   48.35   48.35   48.51   48.49   48.38   48.38
   48.28   48.93   49.87   50.24   50.09   50.16   50.00
 -957.80 -954.45 -954.13 -952.92 -952.09 -951.70 -951.09 -951.06 -951.27 -951.27
 -951.52 -951.56 -951.67 -951.54 -951.69 -951.93 -951.69 -951.80 -951.77   40.23
   40.45   40.41   40.24   40.38   40.35 -951.65 -951.49 -951.51 -951.62 -951.62
 -951.72 -951.07 -950.13 -949.76 -949.91 -949.84 -950.00
BR Coef=-1 , 0 , 0 ,, 0 ,,,0.8,0,1,0,
WSPro=,,,, 1 ,,,, 0 ,,,, 0 ,,,,-1 ,-1 ,-1 , 0 , 0 , 0 , 0 , 0
BC Design=,, 0 ,, 0 ,,,,,,

Type RM Length L Ch R = 1 ,4387.557,106.556700,106.556700,106.556700
XS GIS Cut Line= 3
882951.544952755796761.667066808882262.887545347796038.732593874
881860.911049621795624.291710683
#Sta/Elev= 30
8854.46859.18257 8918.9235.270478932.73133.700068950.94838.612698979.944 41.0749
9052.43637.987169236.57137.680299255.41332.429639313.40734.688619719.36133.41745
9733.85939.740289762.85638.931749806.35146.477869849.84648.20418 9872.04 47.2509
9907.32739.108299927.76440.862529955.62639.809189979.14232.49891 9997.4229.49711
10067.0831.3151310108.8741.3991310234.2538.7616610295.1340.3826410317.8344.11412
10331.7751.5073910352.5853.4733610373.56 66.639710381.31 69.061510430.2769.89602
#Mann= 3 , 0 , 0
8854.468  0.0412       08854.468  0.0412       010430.27  0.0412       0
#XS Ineff= 2 , 0
       0                10148.65       0
Bank Sta=8854.468,10430.27
Exp/Cntr=0.3,0.1

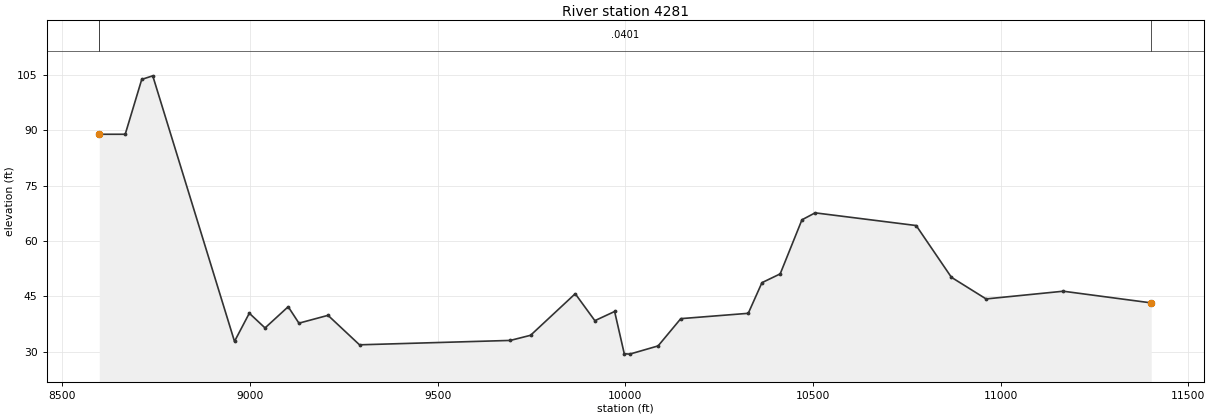
Type RM Length L Ch R = 1 ,    4281,0.000000,0.000000,0.000000
XS GIS Cut Line= 6
883211.670298256796905.874103727882496.537748931796161.837849176
 882218.08127253795841.726900665 881779.46540651795188.236649273
881644.906547196794944.602009848881532.906504812794687.013188836
#Sta/Elev= 30
8598.52488.910588667.68888.910588711.699103.76638741.053104.73048958.88532.82865
8998.30340.459189040.25436.474089101.946 42.21829130.55837.766089208.05739.88496
9291.95931.905979693.79533.094669747.78934.486049866.75745.736359919.08738.44312
9971.70740.927349997.43529.4852310011.9229.3843510087.5731.6077210148.0338.98893
 10327.840.4337310364.2448.7285210412.8751.1100310470.8165.7458310505.9867.63442
10775.1964.1979610869.0850.1867110961.5244.3266511167.1446.4155411401.4743.25812
#Mann= 3 , 0 , 0
8598.524  0.0401       08598.524  0.0401       011401.47  0.0401       0
#XS Ineff= 2 , 0
       0                10178.92       0
Bank Sta=8598.524,11401.47
Exp/Cntr=0.3,0.1